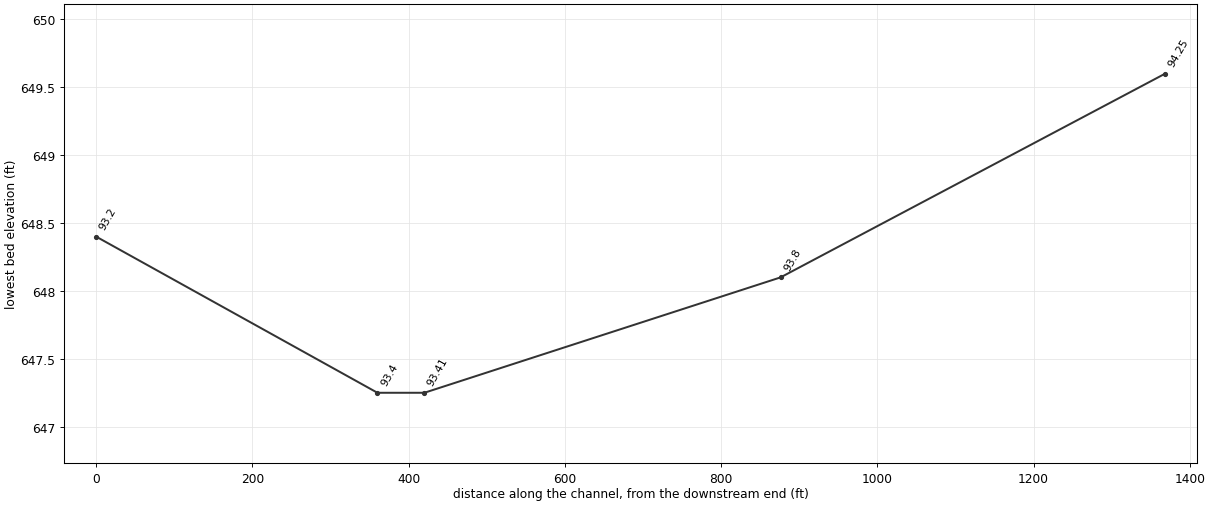
--- Output5s.prj (project) ---

Proj Title=Output Analysis Solution # 5
Current Plan=p01
Default Exp/Contr=0.3,0.1
English Units
Geom File=g01
Flow File=f01
Plan File=p01
BEGIN DESCRIPTION:
END DESCRIPTION:

--- Output5s.p01 (plan) ---

Plan Title=Imported Plan 01
Short Identifier=Imported Pla
Geom File=g01
Flow File=f01
Multiple Comp Mode
Subcritical Flow
K Sum by GR= 0
Std Step Tol= .01
Critical Tol= .01
Num of Std Step Trials= 20
Max Error Tol= .3
Flow Tol Ratio= .001
Log Output Level= 0
Friction Slope Method= 1
Parabolic Critical Depth

--- Output5s.f01 (steady flow) ---

Flow Title=Imported Flow 01
Number of Profiles= 1
Profile Names=PF#1
River Rch & RM=1,1               ,94.25
    5700
Boundary for River Rch & Prof#=1,1               , 1
Up Type= 0
Dn Type= 1
Dn Known WS=659

--- Output5s.g01 (geometry) ---

Geom Title=Imported Geom 01

River Reach=1               ,1
Reach XY= 2
              .5              .9              .5              .1

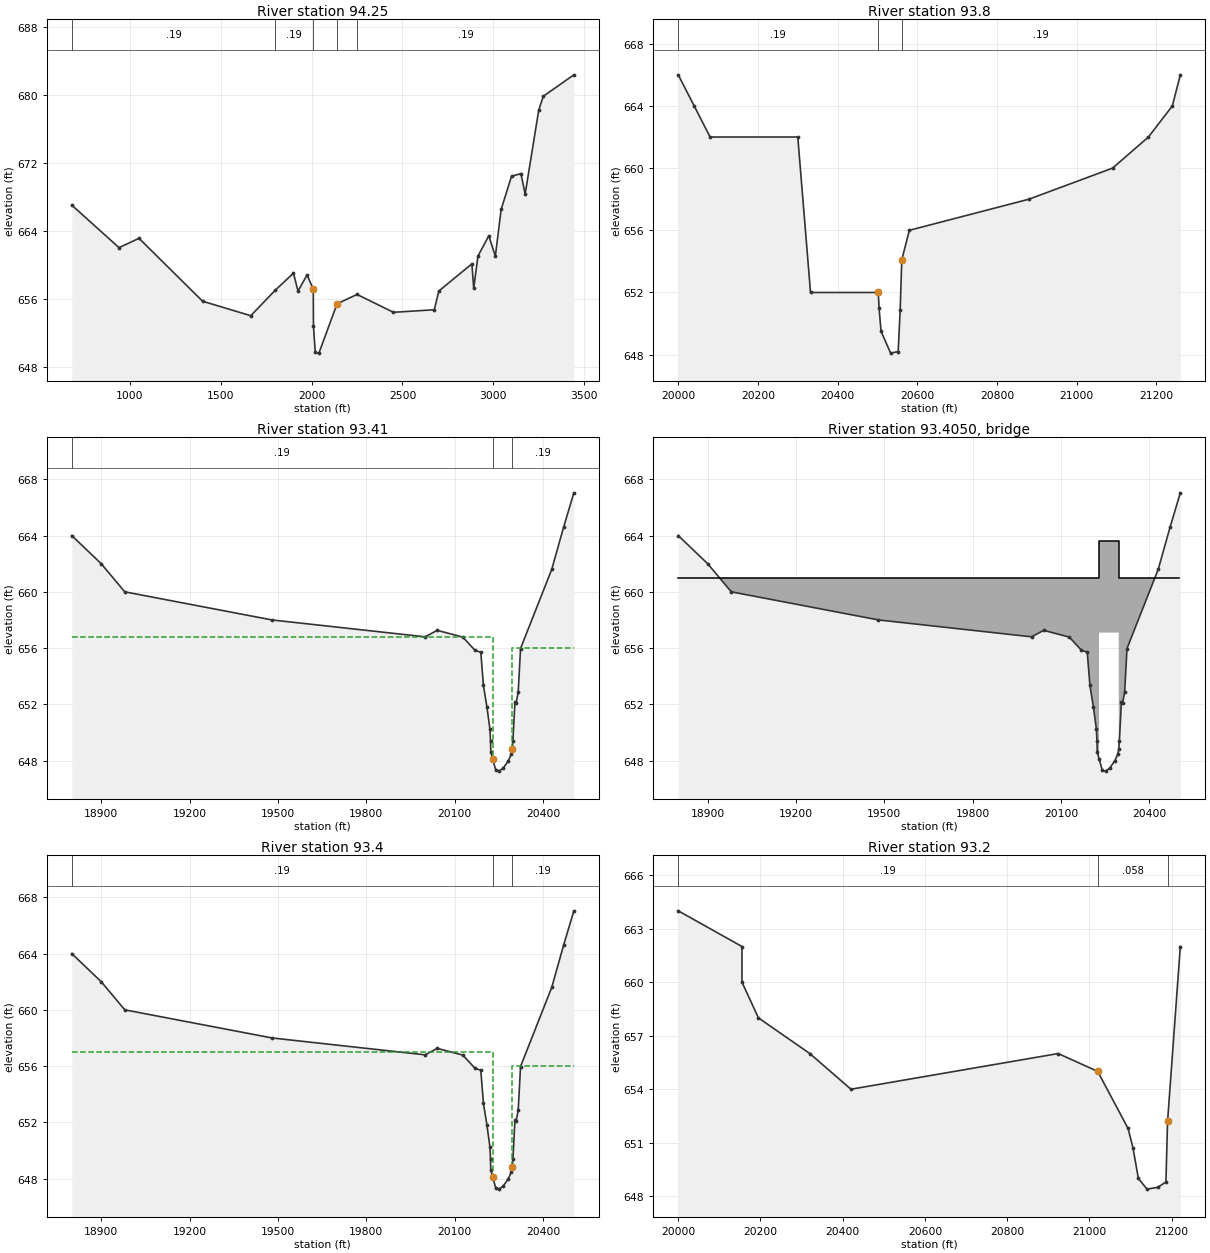
Type RM Length L Ch R = 1 ,94.25   ,450.67,492,448
BEGIN DESCRIPTION:
94.25
END DESCRIPTION:
#Sta/Elev= 30
     680     667     940     662    1050   663.1    1400   655.7    1665     654
    1800     657    1900     659    1925   656.9    1975   658.8    2009   657.1
    2010   652.8    2020   649.7    2040   649.6    2140   655.4    2250   656.5
    2450   654.4    2675   654.7    2700   656.9    2882   660.1    2892   657.2
    2915     661    2975   663.4    3011     661    3043   666.5    3100   670.4
    3152   670.7    3175   668.3    3250   678.2    3275   679.8    3443  682.32
#Mann= 5 , 1 , 0
     680     .19       0    1800     .19       0    2009    .058       0
    2140     .19       0    2250     .19       0
Bank Sta=2009,2140
Exp/Cntr=0.5,0.3

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
Type RM Length L Ch R = 1 ,93.8    ,377.6,456,432
BEGIN DESCRIPTION:
93.8
END DESCRIPTION:
#Sta/Elev= 18
   20000     666   20040     664   20080     662   20300     662   20332     652
   20502     652   20504     651   20509   649.5   20533   648.1   20552   648.2
   20557   650.9   20561   654.1   20580     656   20880     658   21090     660
   21180     662   21240     664   21260     666
#Mann= 3 , 0 , 0
   20000     .19       0   20502    .058       0   20561     .19       0
Bank Sta=20502,20561
Exp/Cntr=0.5,0.3

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
Type RM Length L Ch R = 1 ,93.41   ,60,60,60
BEGIN DESCRIPTION:
93.41
END DESCRIPTION:
#Sta/Elev= 29
   18800     664   18900     662   18980     660   19480     658   20000   656.8
   20041  657.26   20128  656.78   20169  655.85   20189   655.7   20198  653.35
   20210  651.79   20220  650.24   20222  649.37   20223   648.6   20229  648.14
   20240  647.31   20251  647.25   20265  647.46   20283     648   20293  648.49
   20296  648.82   20298  649.36   20305  652.16   20309   652.1   20316  652.85
   20324  655.97   20430   661.6   20470  664.58   20505  667.04
#Mann= 3 , 0 , 0
   18800     .19       0   20229    .058       0   20296     .19       0
#XS Ineff= 2 , 0
           20229  656.78   20296             656
Bank Sta=20229,20296
Exp/Cntr=0.5,0.3

Type RM Length L Ch R = 3 ,93.4050 ,,,
BEGIN DESCRIPTION:
Bridge # 68
END DESCRIPTION:
Bridge Culvert--1,-1,-1,-1
Deck Dist Width WeirC Skew NumUp NumDn MinLoCord MaxHiCord MaxSubmerge Is_Ogee
5,50,2.8,,12,12,657.1,,0.95,0,,,,
   18800   20128   20189   20229   20229   20296   20296   20298   20305   20316
   20324   20500
     661     661     661     661   663.6   663.6     661     661     661     661
     661     661
     640     640     640     640   657.1   657.1     640     640     640     640
     640     640
   18800   20128   20189   20229   20229   20296   20296   20298   20305   20316
   20324   20500
     661     661     661     661   663.6   663.6     661     661     661     661
     661     661
     640     640     640     640   657.1   657.1     640     640     640     640
     640     640
BR Coef=-1 , 0 , 0 ,0.9, 0 ,,,0.8,0,2,1,656
WSPro=,,,, 1 ,,,, 0 ,,,, 0 ,,,,-1 ,-1 ,-1 , 0 , 0 , 0 , 0 , 0

Type RM Length L Ch R = 1 ,93.4    ,376,360,360
BEGIN DESCRIPTION:
93.4
END DESCRIPTION:
#Sta/Elev= 29
   18800     664   18900     662   18980     660   19480     658   20000   656.8
   20041  657.26   20128  656.78   20169  655.85   20189   655.7   20198  653.35
   20210  651.79   20220  650.24   20222  649.37   20223   648.6   20229  648.14
   20240  647.31   20251  647.25   20265  647.46   20283     648   20293  648.49
   20296  648.82   20298  649.36   20305  652.16   20309   652.1   20316  652.85
   20324  655.97   20430   661.6   20470  664.58   20505  667.04
#Mann= 3 , 0 , 0
   18800     .19       0   20229    .058       0   20296     .19       0
#XS Ineff= 2 , 0
           20229     657   20296             656
Bank Sta=20229,20296
Exp/Cntr=0.5,0.3

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
Type RM Length L Ch R = 1 ,93.2    ,560,472,416
BEGIN DESCRIPTION:
93.2
END DESCRIPTION:
#Sta/Elev= 16
   20000     664   20155     662   20155     660   20195     658   20320     656
   20420     654   20924     656   21020     655   21094   651.8   21106   650.7
   21119     649   21140   648.4   21166   648.5   21186   648.8   21190   652.2
   21221     662
#Mann= 3 , 0 , 0
   20000     .19       0   21020    .058       0   21190     .19       0
Bank Sta=21020,21190
Exp/Cntr=0.5,0.3

Chan Stop Cuts=-1