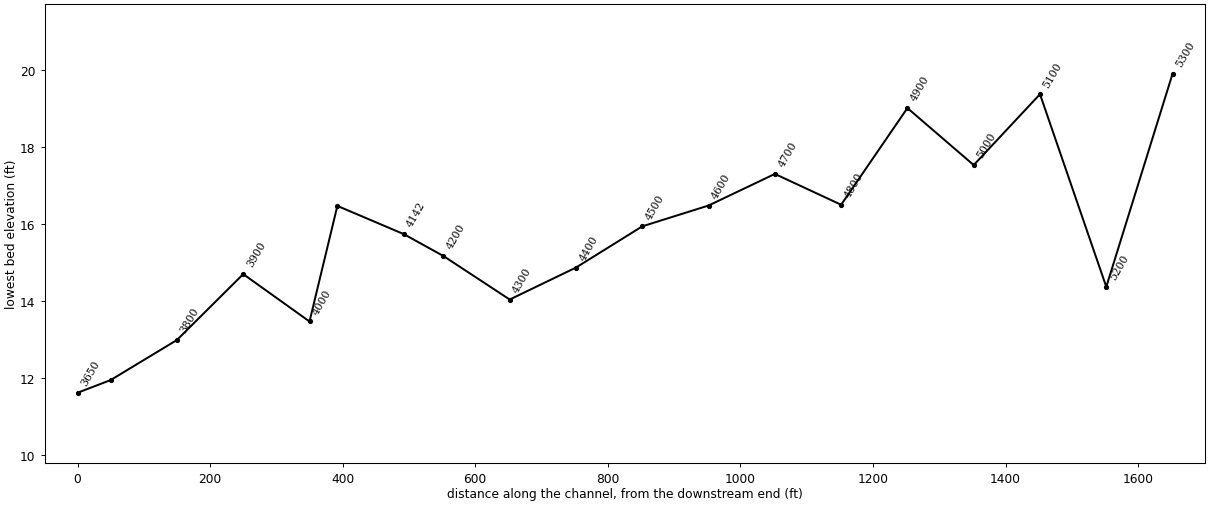
--- Wrk3_sol.prj (project) ---

Proj Title=Napa Creek
Current Plan=p03
Default Exp/Contr=0.3,0.1
English Units
Geom File=g03
Geom File=g02
Geom File=g01
Flow File=f01
Plan File=p03
Plan File=p02
Plan File=p01
BEGIN DESCRIPTION:
END DESCRIPTION:

--- Wrk3_sol.p03 (plan) ---

Plan Title=Napa Creek - with relief culverts
Short Identifier=relief culv
Geom File=g03
Flow File=f01
Multiple Comp Mode
Subcritical Flow
K Sum by GR= 0
Std Step Tol= .01
Critical Tol= .01
Num of Std Step Trials= 20
Max Error Tol= .3
Flow Tol Ratio= .001
Log Output Level= 0
Friction Slope Method= 1
Parabolic Critical Depth

--- Wrk3_sol.p01 (plan) ---

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Plan Title=Napa Creek - existing conditions
Short Identifier=existing
Geom File=g01
Flow File=f01

--- Wrk3_sol.p02 (plan) ---

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Plan Title=Napa Creek - with culverts
Short Identifier=culverts
Geom File=g02
Flow File=f01

--- Wrk3_sol.f01 (steady flow) ---

Flow Title=Napa Creek - Flood Flows
Number of Flows and Profiles and Boundary= 1, 3, 1
Rch & RM=Napa Cr.    ,5300
    2500    4000    6500
Boundary for Rch & Prof#=Napa Cr.    , 1
Up Type= 0
Up Value=0
Dn Type= 2
Dn Value=0
Boundary for Rch & Prof#=Napa Cr.    , 2
Up Type= 0
Up Value=0
Dn Type= 2
Dn Value=0
Boundary for Rch & Prof#=Napa Cr.    , 3
Up Type= 0
Up Value=0
Dn Type= 2
Dn Value=0

--- Wrk3_sol.g03 (geometry) ---

Geom Title=final with relief culverts

River Reach=Napa Cr.        ,Napa Cr.
Reach XY= 2
              .5              .9              .5              .1

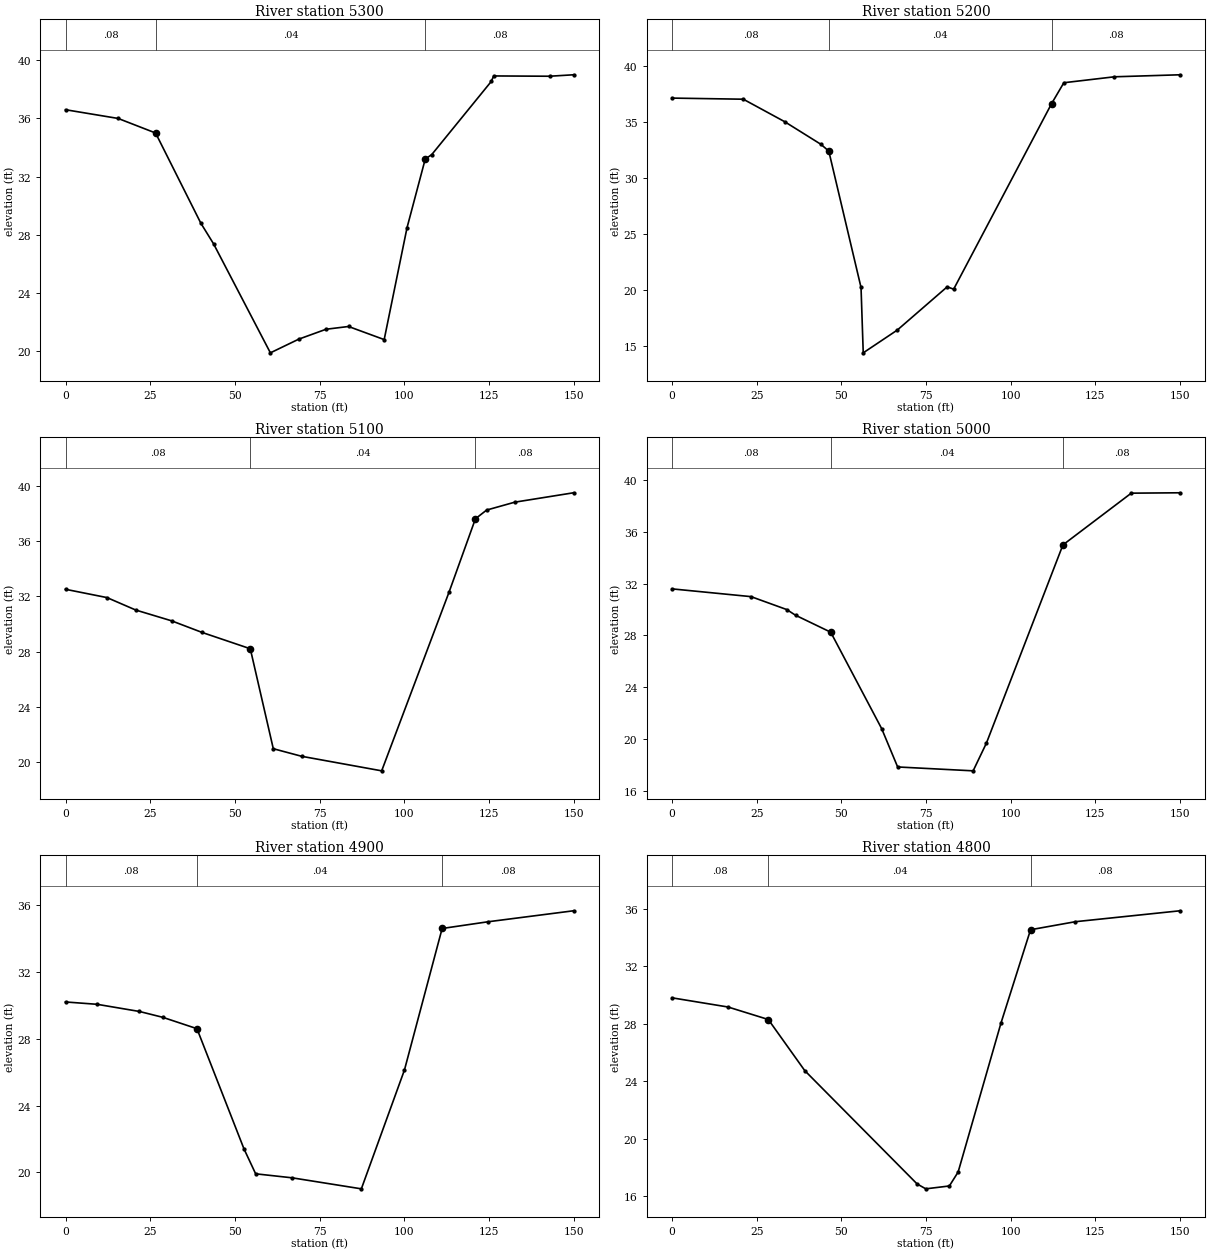
Type RM Length L Ch R = 1 ,5300    ,100,100,100
BEGIN DESCRIPTION:
5300
END DESCRIPTION:
#Sta/Elev= 17
       0    36.6   15.55      36    26.6      35   39.97    28.8   43.71   27.39
   60.49    19.9   68.87   20.84   76.92   21.52   83.56   21.71   94.09   20.81
  100.84    28.5  106.21   33.21  108.14   33.52   125.7   38.54  126.42   38.92
  142.91    38.9     150      39
#Mann= 3 , 0 , 0
       0     .08       0    26.6     .04       0  106.21     .08       0
Bank Sta=26.6,106.21
Exp/Cntr=0.3,0.1

Type RM Length L Ch R = 1 ,5200    ,100,100,100
BEGIN DESCRIPTION:
5200
END DESCRIPTION:
#Sta/Elev= 14
       0    37.1   21.06      37   33.24      35      44   32.97    46.3   32.37
   55.82    20.2   56.47   14.37   66.52    16.4   81.26   20.26   83.17   20.05
  112.07    36.6   115.7   38.47  130.63      39     150   39.18
#Mann= 3 , 0 , 0
       0     .08       0    46.3     .04       0  112.07     .08       0
Bank Sta=46.3,112.07
Exp/Cntr=0.3,0.1

Type RM Length L Ch R = 1 ,5100    ,100,100,100
BEGIN DESCRIPTION:
5100
END DESCRIPTION:
#Sta/Elev= 14
       0    32.5   12.25    31.9   20.74      31   31.31   30.22   40.32   29.38
   54.56    28.2   61.35   20.97   69.75   20.42   93.35   19.37  113.28   32.32
  121.03    37.6  124.34   38.23  132.64    38.8     150   39.48
#Mann= 3 , 0 , 0
       0     .08       0   54.56     .04       0  121.03     .08       0
Bank Sta=54.56,121.03
Exp/Cntr=0.3,0.1

Type RM Length L Ch R = 1 ,5000    ,100,100,100
BEGIN DESCRIPTION:
5000
END DESCRIPTION:
#Sta/Elev= 12
       0    31.6   23.34      31   33.89      30   36.49   29.56   46.87   28.25
    61.9    20.8   66.63   17.83   88.92   17.53   92.85   19.68  115.43      35
  135.61      39     150   39.03
#Mann= 3 , 0 , 0
       0     .08       0   46.87     .04       0  115.43     .08       0
Bank Sta=46.87,115.43
Exp/Cntr=0.3,0.1

Type RM Length L Ch R = 1 ,4900    ,100,100,100
BEGIN DESCRIPTION:
4900
END DESCRIPTION:
#Sta/Elev= 13
       0    30.2    9.32   30.06   21.84   29.63   28.73   29.28   38.81    28.6
    52.7    21.4   56.14   19.91   66.91   19.67   87.35   19.01  100.08   26.13
   111.2    34.6  124.68      35     150   35.66
#Mann= 3 , 0 , 0
       0     .08       0   38.81     .04       0   111.2     .08       0
Bank Sta=38.81,111.2
Exp/Cntr=0.3,0.1

Type RM Length L Ch R = 1 ,4800    ,100,100,100
BEGIN DESCRIPTION:
4800
END DESCRIPTION:
#Sta/Elev= 12
       0    29.8   16.56   29.16   28.44   28.29   39.21   24.73   72.38   16.84
   74.94    16.5    81.9    16.7   84.49   17.67   97.15   28.05  105.87   34.54
  119.12    35.1     150   35.86
#Mann= 3 , 0 , 0
       0     .08       0   28.44     .04       0  105.87     .08       0
Bank Sta=28.44,105.87
Exp/Cntr=0.3,0.1

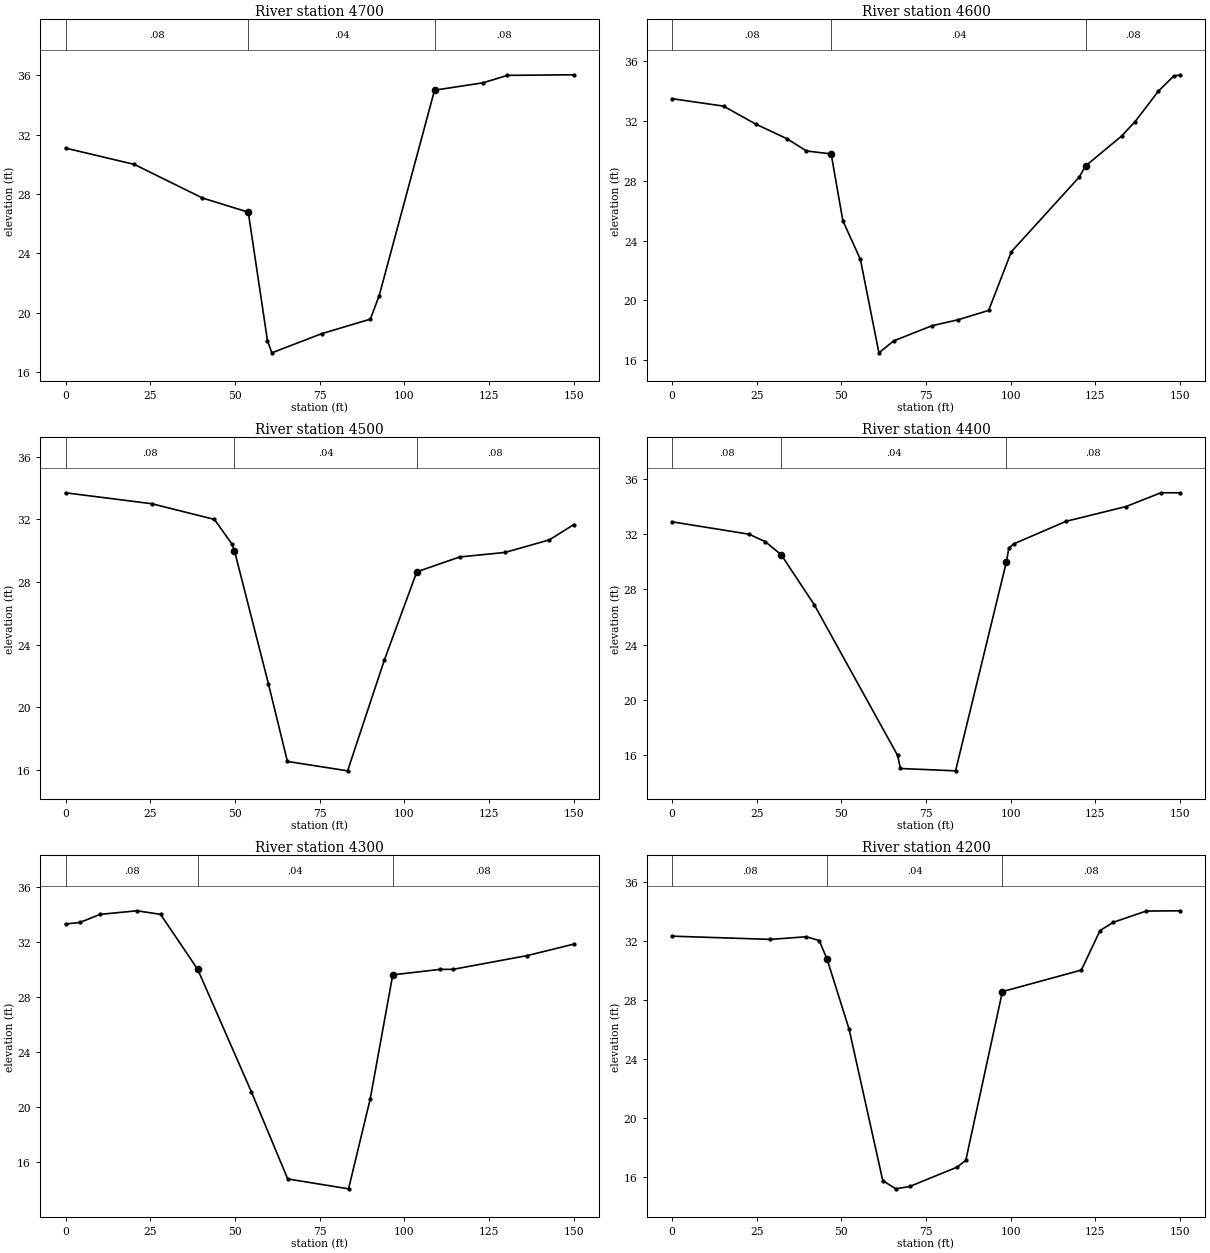
Type RM Length L Ch R = 1 ,4700    ,100,100,100
BEGIN DESCRIPTION:
4700
END DESCRIPTION:
#Sta/Elev= 13
       0    31.1   20.32      30   40.38   27.74   53.96   26.78   59.62   18.13
   60.92    17.3    75.6   18.59   90.01   19.57   92.62   21.16  108.96      35
  123.28    35.5  130.47      36     150   36.04
#Mann= 3 , 0 , 0
       0     .08       0   53.96     .04       0  108.96     .08       0
Bank Sta=53.96,108.96
Exp/Cntr=0.3,0.1

Type RM Length L Ch R = 1 ,4600    ,100,100,100
BEGIN DESCRIPTION:
4600
END DESCRIPTION:
#Sta/Elev= 21
       0    33.5   15.23      33   24.71    31.8   34.03   30.81   39.68      30
      47    29.8   50.46   25.32   55.63   22.74    61.1   16.48   65.45   17.28
   76.82    18.3   84.41   18.69    93.5   19.32   100.2   23.25  120.25   28.25
  122.13      29  132.77      31  136.76   31.97   143.6      34  148.08      35
     150    35.1
#Mann= 3 , 0 , 0
       0     .08       0      47     .04       0  122.13     .08       0
Bank Sta=47,122.13
Exp/Cntr=0.3,0.1

Type RM Length L Ch R = 1 ,4500    ,100,100,100
BEGIN DESCRIPTION:
4500
END DESCRIPTION:
#Sta/Elev= 14
       0    33.7   25.48      33   43.95      32   49.08   30.45   49.88      30
   59.91    21.5   65.52   16.54   83.29   15.94    94.1   22.99  103.72   28.65
  116.36    29.6  129.77   29.89  142.85   30.69     150   31.66
#Mann= 3 , 0 , 0
       0     .08       0   49.88     .04       0  103.72     .08       0
Bank Sta=49.88,103.72
Exp/Cntr=0.3,0.1

Type RM Length L Ch R = 1 ,4400    ,100,100,100
BEGIN DESCRIPTION:
4400
END DESCRIPTION:
#Sta/Elev= 15
       0    32.9   22.79      32   27.55   31.46   32.23   30.52      42    26.9
   66.59      16   67.47   15.04   83.73   14.87   98.73   29.99   99.46      31
  100.91    31.3   116.3   32.93  134.02      34  144.36      35     150      35
#Mann= 3 , 0 , 0
       0     .08       0   32.23     .04       0   98.73     .08       0
Bank Sta=32.23,98.73
Exp/Cntr=0.3,0.1

Type RM Length L Ch R = 1 ,4300    ,100,100,100
BEGIN DESCRIPTION:
4300
END DESCRIPTION:
#Sta/Elev= 15
       0    33.3    4.26   33.41   10.22      34    21.1   34.26   28.06      34
   39.03      30    54.9   21.08   65.61   14.76   83.57   14.04   89.95   20.56
   96.62    29.6   110.6      30  114.38      30  136.28      31     150   31.83
#Mann= 3 , 0 , 0
       0     .08       0   39.03     .04       0   96.62     .08       0
Bank Sta=39.03,96.62
Exp/Cntr=0.3,0.1

Type RM Length L Ch R = 1 ,4200    ,60,60,60
BEGIN DESCRIPTION:
4200
END DESCRIPTION:
#Sta/Elev= 17
       0    32.3   29.08   32.08   39.69   32.26   43.47      32   45.78   30.75
   52.29      26   62.24   15.73   66.05   15.17    70.2   15.33   84.18   16.64
   86.75    17.1   97.56   28.54  120.87      30  126.39   32.68  130.32   33.24
  139.99      34     150   34.02
#Mann= 3 , 0 , 0
       0     .08       0   45.78     .04       0   97.56     .08       0
Bank Sta=45.78,97.56
Exp/Cntr=0.3,0.1

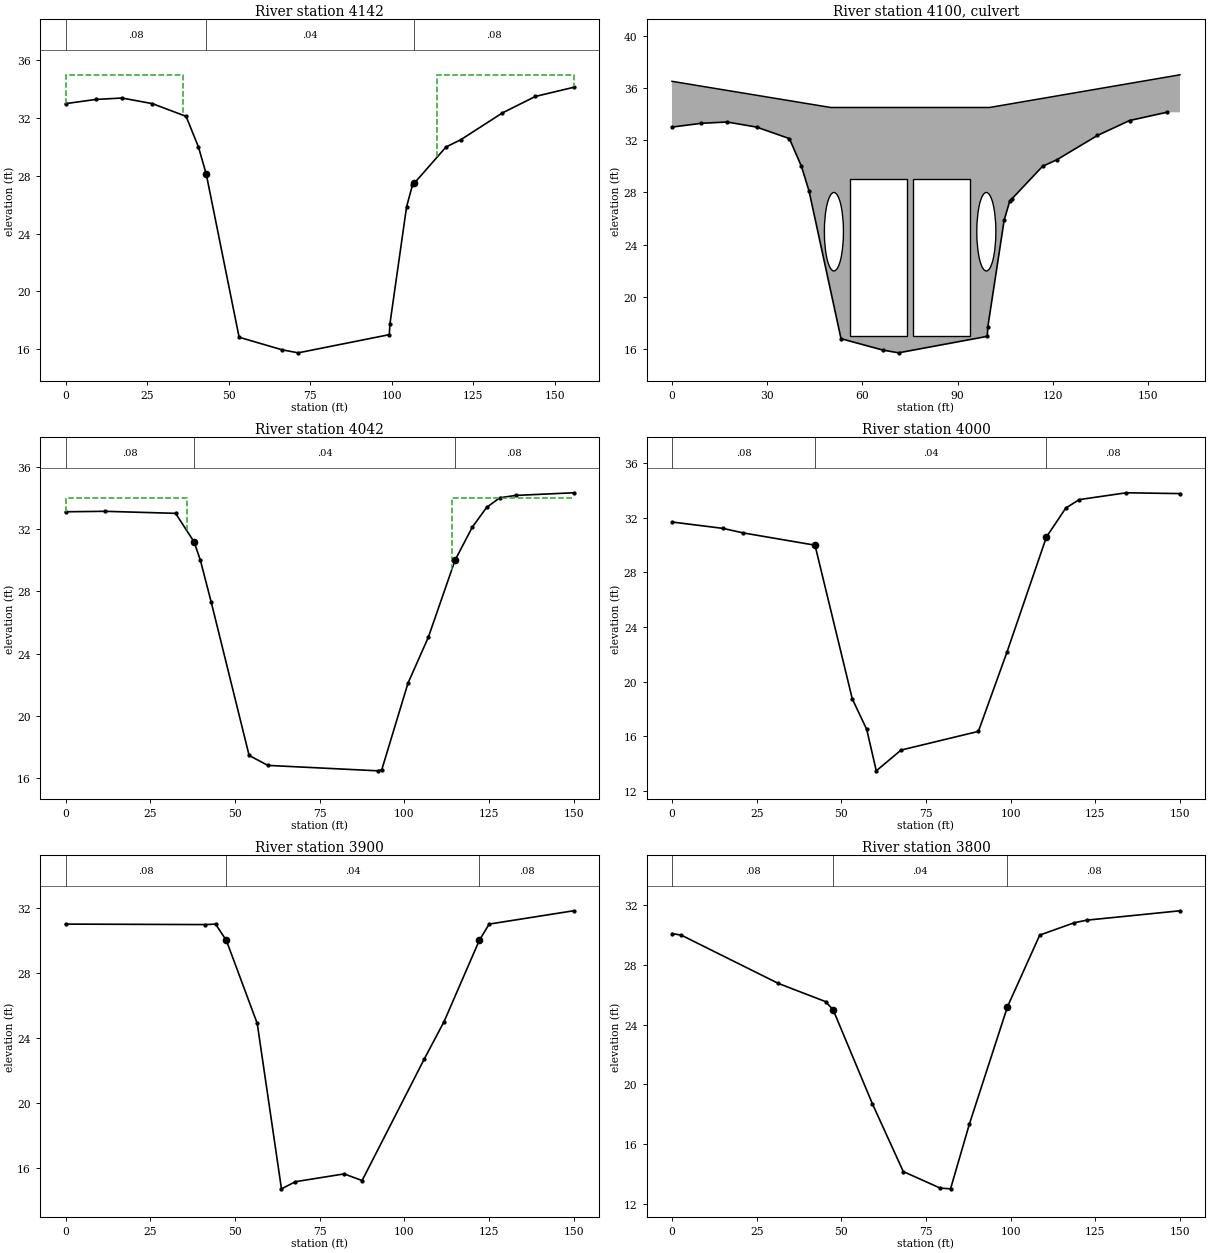
Type RM Length L Ch R = 1 ,4142    ,100,100,100
BEGIN DESCRIPTION:
4142
END DESCRIPTION:
#Sta/Elev= 20
       0      33    9.26   33.29   17.33   33.39   26.66      33   36.98   32.12
   40.77      30   43.17   28.11   53.24   16.82   66.43   15.95   71.35   15.74
    99.3      17   99.49   17.75   104.6   25.86   106.4   27.36     107    27.5
   116.7      30   121.2    30.5     134   32.36   144.1    33.5   155.8   34.13
#Mann= 3 , 0 , 0
       0     .08       0   43.17     .04       0     107     .08       0
#XS Ineff= 2 , 0
              36      35     114              35
Bank Sta=43.17,107
Exp/Cntr=0.5,0.3

Type RM Length L Ch R = 2 ,4100    ,,,
BEGIN DESCRIPTION:
Box with relief culverts
END DESCRIPTION:
Bridge Culvert--1,-1,-1,-1
Deck Dist Width WeirC Skew NumUp NumDn MinLoCord MaxHiCord MaxSubmerge Is_Ogee
20,60,2.6,,4,4,,,0.95,0,1,1,,
       0      50     100     160
    36.5    34.5    34.5      37
                                
       0      50     100     160
    36.5    34.5    34.5      37
                                
Multiple Barrel Culv=1,6,,80,0.026,0.5,1,2,1,22,21.5, 2,Culvert #2  , 0 ,10
      51      51      99      99
Multiple Barrel Culv=2,12,18,80,0.017,0.35,1,10,1,17,16.7, 2,Culvert #1  , 0 ,10
      65      65      85      85

Type RM Length L Ch R = 1 ,4042    ,42,42,42
BEGIN DESCRIPTION:
4060
END DESCRIPTION:
#Sta/Elev= 18
       0    33.1   11.74   33.13    32.5      33   37.95   31.17   39.81      30
   43.02    27.3   54.21   17.46   59.73   16.82   92.32   16.47   93.39   16.55
  101.12    22.1   107.1   25.03  115.03      30   120.1   32.11  124.33   33.38
  128.23      34  132.91   34.15     150   34.32
#Mann= 3 , 0 , 0
       0     .08       0   37.95     .04       0  115.03     .08       0
#XS Ineff= 2 , 0
              36      34     114              34
Bank Sta=37.95,115.03
Exp/Cntr=0.3,0.1

Type RM Length L Ch R = 1 ,4000    ,100,100,100
BEGIN DESCRIPTION:
4000
END DESCRIPTION:
#Sta/Elev= 15
       0    31.7   15.06   31.23   21.03    30.9   42.23      30   53.24   18.74
   57.51    16.5   60.32   13.47   67.63   14.99   90.47   16.36   98.87   22.14
  110.56    30.6  116.27   32.72  120.24   33.34  134.15   33.84     150   33.78
#Mann= 3 , 0 , 0
       0     .08       0   42.23     .04       0  110.56     .08       0
Bank Sta=42.23,110.56
Exp/Cntr=0.3,0.1

Type RM Length L Ch R = 1 ,3900    ,100,100,100
BEGIN DESCRIPTION:
3900
END DESCRIPTION:
#Sta/Elev= 14
       0      31   41.28   30.97    44.3      31   47.48      30   56.61   24.88
   63.76    14.7    67.9   15.14   82.27   15.62   87.57   15.21  105.94    22.7
  111.78      25  122.18      30  125.08      31     150   31.82
#Mann= 3 , 0 , 0
       0     .08       0   47.48     .04       0  122.18     .08       0
Bank Sta=47.48,122.18
Exp/Cntr=0.3,0.1

Type RM Length L Ch R = 1 ,3800    ,100,100,100
BEGIN DESCRIPTION:
3800
END DESCRIPTION:
#Sta/Elev= 15
       0    30.1    2.72      30   31.41   26.76   45.35   25.54   47.57      25
   59.16    18.7   68.29   14.15   79.19   13.04   82.25   12.99   87.78   17.31
   99.06    25.2  108.58      30   118.8   30.83  122.45      31     150   31.63
#Mann= 3 , 0 , 0
       0     .08       0   47.57     .04       0   99.06     .08       0
Bank Sta=47.57,99.06
Exp/Cntr=0.3,0.1

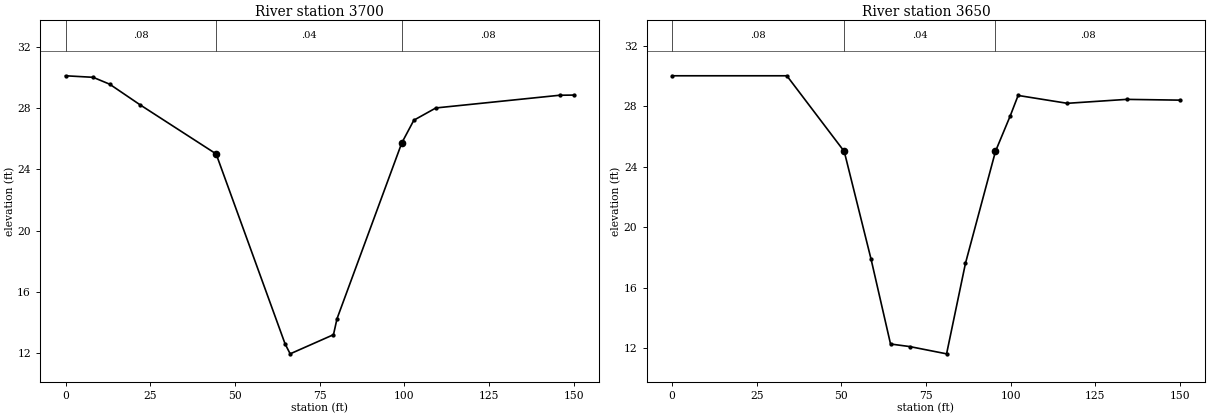
Type RM Length L Ch R = 1 ,3700    ,50,50,50
BEGIN DESCRIPTION:
3700
END DESCRIPTION:
#Sta/Elev= 14
       0    30.1    8.15      30   13.05   29.55   21.98   28.21   44.47      25
   64.83    12.6   66.33   11.95   79.12    13.2   80.16   14.24   99.29   25.72
  102.85    27.2  109.35      28  145.94   28.83     150   28.84
#Mann= 3 , 0 , 0
       0     .08       0   44.47     .04       0   99.29     .08       0
Bank Sta=44.47,99.29
Exp/Cntr=0.3,0.1

Type RM Length L Ch R = 1 ,3650    ,300,300,300
BEGIN DESCRIPTION:
3650
END DESCRIPTION:
#Sta/Elev= 14
       0      30   33.92      30   50.86      25    58.8   17.86   64.53   12.27
   70.21    12.1   81.08   11.62   86.66   17.61   95.51      25   99.91   27.37
   102.2    28.7  116.71   28.18   134.2   28.44     150   28.39
#Mann= 3 , 0 , 0
       0     .08       0   50.86     .04       0   95.51     .08       0
Bank Sta=50.86,95.51
Exp/Cntr=0.3,0.1

Chan Stop Cuts=-1

--- Wrk3_sol.g01 (geometry) ---

Geom Title=final geometry

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
River Reach=Napa Cr.        ,Napa Cr.

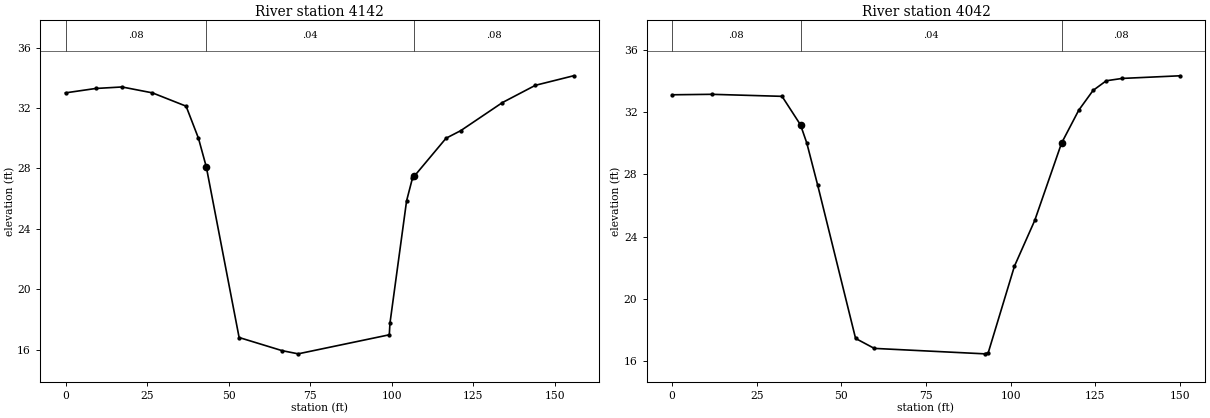
Type RM Length L Ch R = 1 ,4142    ,100,100,100
BEGIN DESCRIPTION:
4142
END DESCRIPTION:
#Sta/Elev= 20
       0      33    9.26   33.29   17.33   33.39   26.66      33   36.98   32.12
   40.77      30   43.17   28.11   53.24   16.82   66.43   15.95   71.35   15.74
    99.3      17   99.49   17.75   104.6   25.86   106.4   27.36     107    27.5
   116.7      30   121.2    30.5     134   32.36   144.1    33.5   155.8   34.13
#Mann= 3 , 0 , 0
       0     .08       0   43.17     .04       0     107     .08       0
Bank Sta=43.17,107
Exp/Cntr=0.5,0.3

Type RM Length L Ch R = 1 ,4042    ,42,42,42
BEGIN DESCRIPTION:
4060
END DESCRIPTION:
#Sta/Elev= 18
       0    33.1   11.74   33.13    32.5      33   37.95   31.17   39.81      30
   43.02    27.3   54.21   17.46   59.73   16.82   92.32   16.47   93.39   16.55
  101.12    22.1   107.1   25.03  115.03      30   120.1   32.11  124.33   33.38
  128.23      34  132.91   34.15     150   34.32
#Mann= 3 , 0 , 0
       0     .08       0   37.95     .04       0  115.03     .08       0
Bank Sta=37.95,115.03
Exp/Cntr=0.3,0.1

--- Wrk3_sol.g02 (geometry) ---

Geom Title=final with culverts

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
River Reach=Napa Cr.        ,Napa Cr.

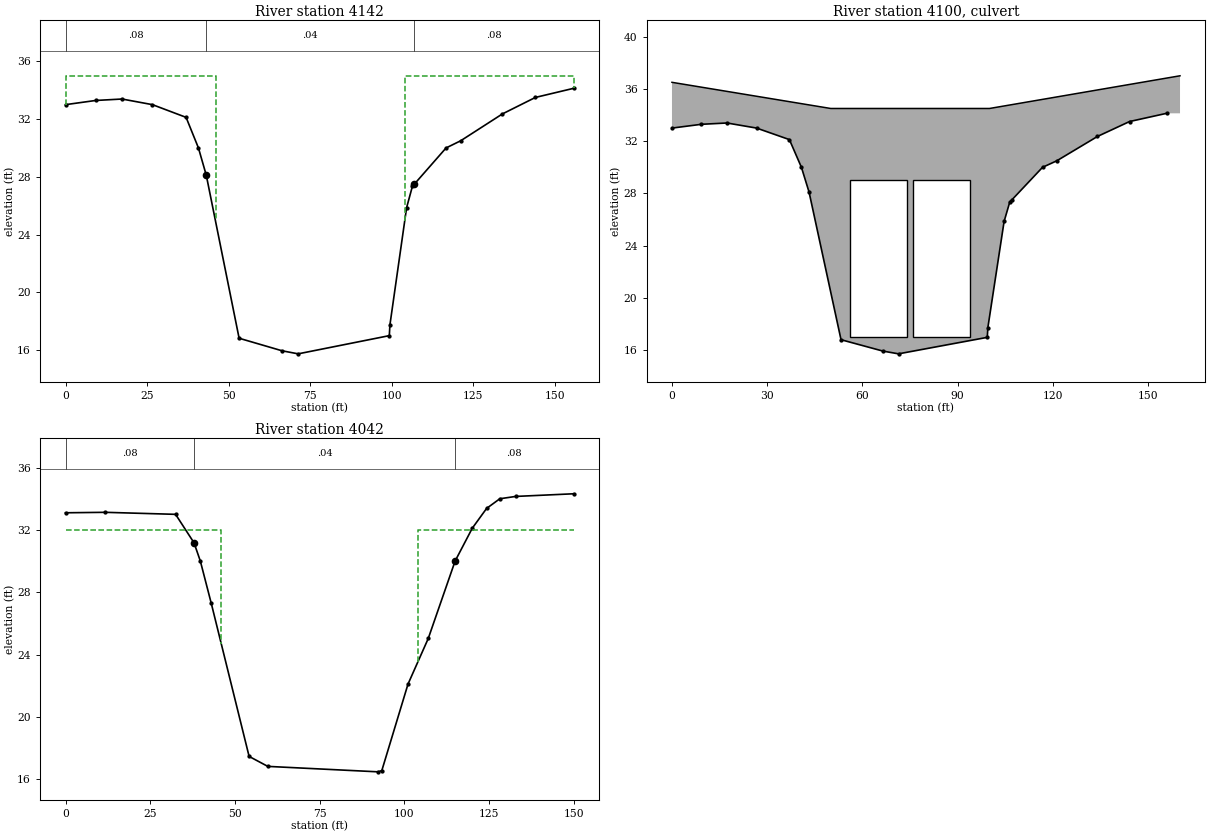
Type RM Length L Ch R = 1 ,4142    ,100,100,100
BEGIN DESCRIPTION:
4142
END DESCRIPTION:
#Sta/Elev= 20
       0      33    9.26   33.29   17.33   33.39   26.66      33   36.98   32.12
   40.77      30   43.17   28.11   53.24   16.82   66.43   15.95   71.35   15.74
    99.3      17   99.49   17.75   104.6   25.86   106.4   27.36     107    27.5
   116.7      30   121.2    30.5     134   32.36   144.1    33.5   155.8   34.13
#Mann= 3 , 0 , 0
       0     .08       0   43.17     .04       0     107     .08       0
#XS Ineff= 2 , 0
              46      35     104              35
Bank Sta=43.17,107
Exp/Cntr=0.5,0.3

Type RM Length L Ch R = 2 ,4100    ,,,
Bridge Culvert--1,-1,-1,-1
Deck Dist Width WeirC Skew NumUp NumDn MinLoCord MaxHiCord MaxSubmerge Is_Ogee
20,60,2.6,,4,4,,,0.95,0,1,1,,
       0      50     100     160
    36.5    34.5    34.5      37
                                
       0      50     100     160
    36.5    34.5    34.5      37
                                
Multiple Barrel Culv=2,12,18,80,0.017,0.35,1,10,1,17,16.7, 2,Culvert #1  , 0 ,10
      65      65      85      85

Type RM Length L Ch R = 1 ,4042    ,42,42,42
BEGIN DESCRIPTION:
4060
END DESCRIPTION:
#Sta/Elev= 18
       0    33.1   11.74   33.13    32.5      33   37.95   31.17   39.81      30
   43.02    27.3   54.21   17.46   59.73   16.82   92.32   16.47   93.39   16.55
  101.12    22.1   107.1   25.03  115.03      30   120.1   32.11  124.33   33.38
  128.23      34  132.91   34.15     150   34.32
#Mann= 3 , 0 , 0
       0     .08       0   37.95     .04       0  115.03     .08       0
#XS Ineff= 2 , 0
              46      32     104              32
Bank Sta=37.95,115.03
Exp/Cntr=0.3,0.1