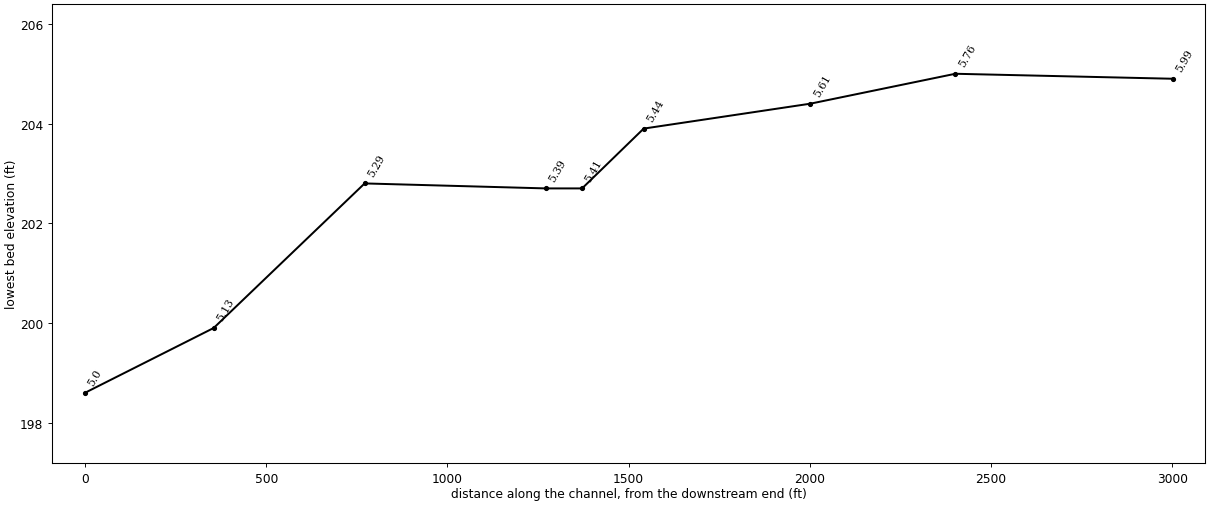
--- Wrk4_sol.prj (project) ---

Proj Title=Mult. Opening Workshop - Beaver Cr.
Current Plan=p02
Default Exp/Contr=.3,.1
English Units
Geom File=g01
Geom File=g02
Flow File=f01
Plan File=p01
Plan File=p02
BEGIN DESCRIPTION:
END DESCRIPTION:

--- Wrk4_sol.p02 (plan) ---

Plan Title=Multiple Opening Bridge
Short Identifier=Mult Open
Geom File=g02
Flow File=f01
Interactive Comp Mode
Subcritical Flow
K Sum by GR= 0
Std Step Tol= 0.01
Critical Tol= 0.01
Num of Std Step Trials= 20
Max Error Tol= 0.3
Flow Tol Ratio= 0.001
Log Output Level= 0
Friction Slope Method= 1
Parabolic Critical Depth
Global Vel Dist= 0 , 0 , 0
Global Log Level= 0
Encroach Param=-1 ,0,0, 0

--- Wrk4_sol.p01 (plan) ---

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Plan Title=Single Bridge Opening
Short Identifier=Single Bridg
Geom File=g01
Flow File=f01
Multiple Comp Mode
Std Step Tol= .01
Critical Tol= .01
Max Error Tol= .3
Flow Tol Ratio= .001

--- Wrk4_sol.f01 (steady flow) ---

Flow Title=Beaver Cr. - 3 Flows
Number of Profiles= 3
Profile Names=PF#1,PF#2,PF#3
River Rch & RM=Beaver Creek,Beaver Creek    ,5.99
    5000   10000   14000
Boundary for River Rch & Prof#=Beaver Creek,Beaver Creek    , 1
Up Type= 0
Dn Type= 1
Dn Known WS=209.5
Boundary for River Rch & Prof#=Beaver Creek,Beaver Creek    , 2
Up Type= 0
Dn Type= 1
Dn Known WS=210.5
Boundary for River Rch & Prof#=Beaver Creek,Beaver Creek    , 3
Up Type= 0
Dn Type= 1
Dn Known WS=211.8

--- Wrk4_sol.g02 (geometry) ---

Geom Title=Beaver Cr. + Mult Opening - P/W

River Reach=Beaver Creek    ,Beaver Creek
Reach XY= 2
        .1176471        .9344262        .8465474        .0901639

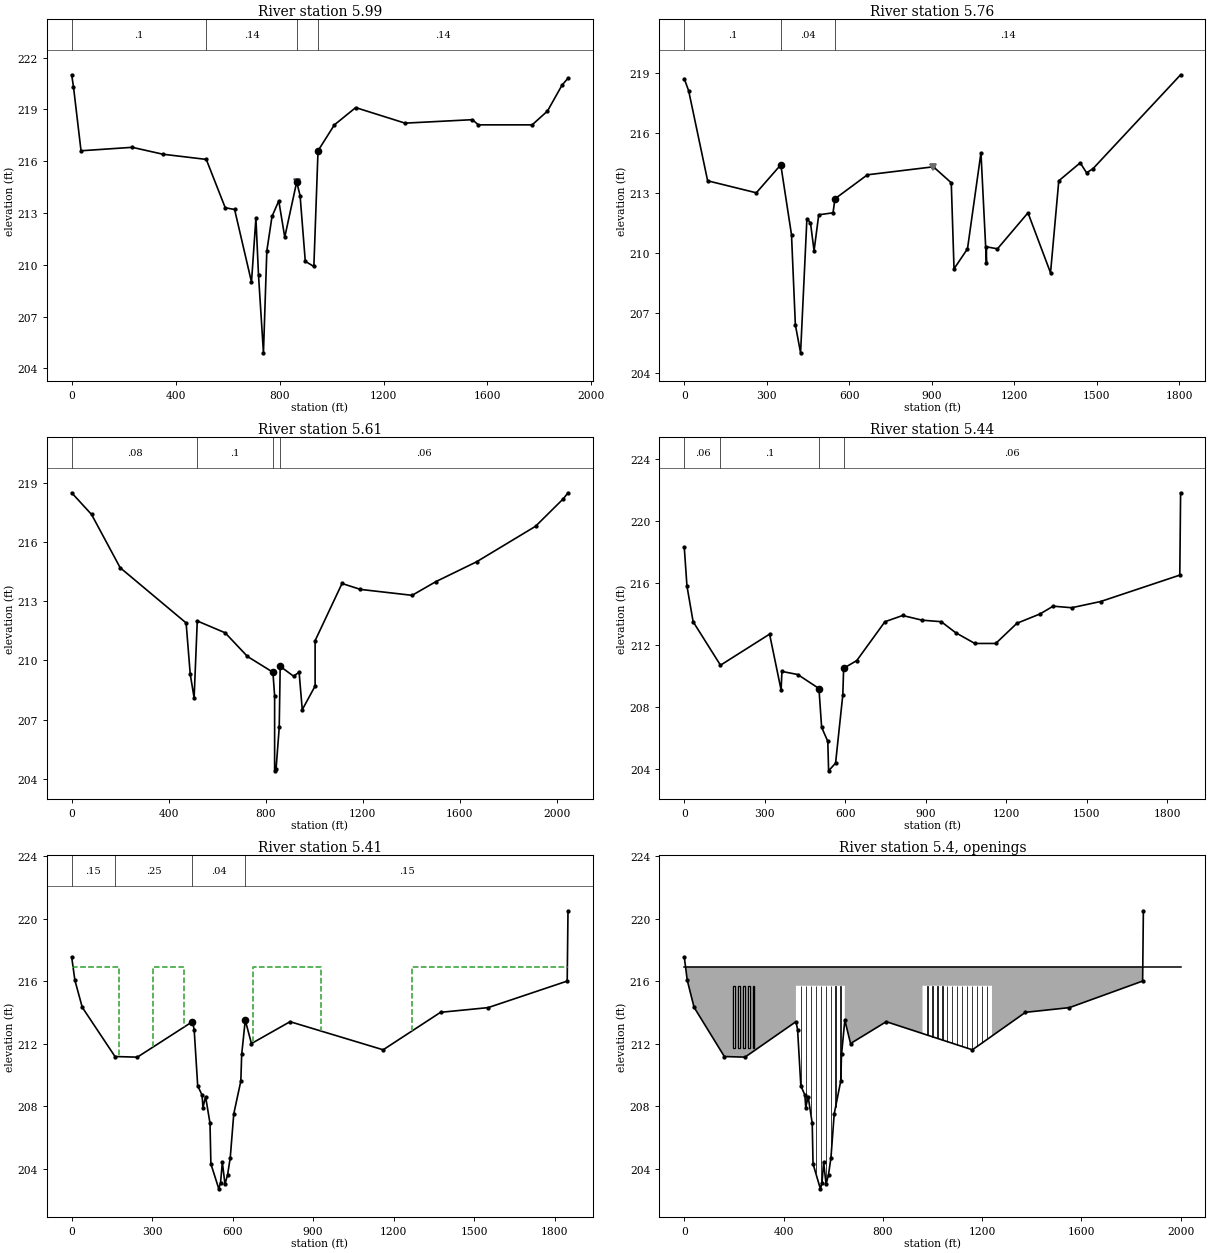
Type RM Length L Ch R = 1 ,5.99    ,440,600,400
BEGIN DESCRIPTION:
Upstream Boundary Cross Section
END DESCRIPTION:
#Sta/Elev= 30
       0     221       7   220.3      36   216.6     233   216.8     351   216.4
     518   216.1     591   213.3     627   213.2     692     209     709   212.7
     719   209.4     738   204.9     751   210.8     771   212.8     797   213.7
     820   211.6     866   214.8     879     214     899   210.2     932   209.9
     948   216.6    1011   218.1    1093   219.1    1283   218.2    1542   218.4
    1565   218.1    1772   218.1    1831   218.9    1887   220.4    1910   220.8
#Mann= 4 , 1 , 0
       0      .1       0     518     .14       0     866     .04       0
     948     .14       0
Levee=-1,866,214.8,0,,
Bank Sta=866,948
Exp/Cntr=.3,.1

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
Type RM Length L Ch R = 1 ,5.76    ,225,400,275
BEGIN DESCRIPTION:
River Station 5.76
END DESCRIPTION:
#Sta/Elev= 30
       0   218.7      16   218.1      85   213.6     262     213     351   214.4
     390   210.9     404   206.4     423     205     446   211.7     459   211.5
     472   210.1     489   211.9     541     212     548   212.7     666   213.9
     906   214.3     971   213.5     981   209.2    1030   210.2    1079     215
    1099   209.5    1099   210.3    1139   210.2    1250     212    1332     209
    1362   213.6    1440   214.5    1463     214    1486   214.2    1805   218.9
#Mann= 3 , 1 , 0
       0      .1       0     351     .04       0     548     .14       0
Levee=0,,,-1,906,214.3
Bank Sta=351,548
Exp/Cntr=.3,.1

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
Type RM Length L Ch R = 1 ,5.61    ,240,460,190
BEGIN DESCRIPTION:
River Station 5.61
END DESCRIPTION:
#Sta/Elev= 28
       0   218.5      82   217.4     200   214.7     472   211.9     489   209.3
     505   208.1     518     212     633   211.4     725   210.2     830   209.4
     837   208.2     837   204.4     843   204.5     856   206.6     860   209.7
     915   209.2     938   209.4     951   207.5    1004   208.7    1004     211
    1115   213.9    1191   213.6    1404   213.3    1503     214    1670     215
    1913   216.8    2028   218.2    2047   218.5
#Mann= 4 , 1 , 0
       0     .08       0     518      .1       0     830     .04       0
     860     .06       0
Bank Sta=830,860
Exp/Cntr=.3,.1

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
Type RM Length L Ch R = 1 ,5.44    ,270,170,500
BEGIN DESCRIPTION:
River Station 5.44
END DESCRIPTION:
#Sta/Elev= 30
       0   218.3      10   215.8      33   213.5     135   210.7     318   212.7
     361   209.1     364   210.3     423   210.1     502   209.2     512   206.7
     535   205.8     538   203.9     564   204.4     591   208.8     594   210.5
     643     211     748   213.5     814   213.9     886   213.6     958   213.5
    1011   212.8    1083   212.1    1161   212.1    1240   213.4    1326     214
    1375   214.5    1444   214.4    1552   214.8    1847   216.5    1850   221.8
#Mann= 4 , 1 , 0
       0     .06       0     135      .1       0     502     .04       0
     594     .06       0
Bank Sta=502,594
Exp/Cntr=.5,.3

Type RM Length L Ch R = 1 ,5.41    ,100,100,100
BEGIN DESCRIPTION:
upstream of bridge embankment
END DESCRIPTION:
#Sta/Elev= 30
       0  217.55      12  216.05    39.5  214.32   161.5  211.17   244.8  211.13
     450   213.4   456.6   212.9   469.7   209.3   486.1   208.7   489.4   207.9
   499.2   208.6   515.6   206.9   518.9   204.3   548.4   202.7     555   203.1
   561.6   204.4   571.4     203   581.2   203.6   591.1   204.7   604.2   207.5
   630.5   209.6   633.7   211.3     647   213.5     670     212     814   213.4
    1161   211.6    1375     214    1552   214.3    1847     216    1850   220.5
#Mann= 4 , 1 , 0
       0     .15       0   161.5     .25       0     450     .04       0
     647     .15       0
#XS Ineff= 4 ,-1
       0     177   216.9     303     420   216.9     677     930   216.9
    1270    1850   216.9
Bank Sta=450,647
Exp/Cntr=.5,.3

Type RM Length L Ch R = 4 ,5.4     ,,,
BEGIN DESCRIPTION:
Bridge # 1
END DESCRIPTION:
Bridge Culvert--1,-1,-1,-1
Deck Dist Width WeirC Skew NumUp NumDn MinLoCord MaxHiCord MaxSubmerge Is_Ogee
30,40,2.6,,10,10,,,.95,0,2,2,,
       0     450     450     647     647     960     960    1240    1240    2000
  216.93  216.93  216.93  216.93  216.93  216.93  216.93  216.93  216.93  216.93
     200     200   215.7   215.7     200     200   215.7   215.7     200     200
       0     450     450     647     647     960     960    1240    1240    2000
  216.93  216.93  216.93  216.93  216.93  216.93  216.93  216.93  216.93  216.93
     200     200   215.7   215.7     200     200   215.7   215.7     200     200
Pier Skew, UpSta & Num, DnSta & Num=,470, 2 ,470, 2 , 0 , 0 , 0 ,,
    1.25    1.25
     200     216
    1.25    1.25
     200     216
Pier Skew, UpSta & Num, DnSta & Num=,490, 2 ,490, 2 , 0 , 0 , 0 ,,
    1.25    1.25
     200     216
    1.25    1.25
     200     216
Pier Skew, UpSta & Num, DnSta & Num=,510, 2 ,510, 2 , 0 , 0 , 0 ,,
    1.25    1.25
     200     216
    1.25    1.25
     200     216
Pier Skew, UpSta & Num, DnSta & Num=,530, 2 ,530, 2 , 0 , 0 , 0 ,,
    1.25    1.25
     200     216
    1.25    1.25
     200     216
Pier Skew, UpSta & Num, DnSta & Num=,550, 2 ,550, 2 , 0 , 0 , 0 ,,
    1.25    1.25
     200     216
    1.25    1.25
     200     216
Pier Skew, UpSta & Num, DnSta & Num=,570, 2 ,570, 2 , 0 , 0 , 0 ,,
    1.25    1.25
     200     216
    1.25    1.25
     200     216
Pier Skew, UpSta & Num, DnSta & Num=,590, 2 ,590, 2 , 0 , 0 , 0 ,,
    1.25    1.25
     200     216
    1.25    1.25
     200     216
Pier Skew, UpSta & Num, DnSta & Num=,610, 2 ,610, 2 , 0 , 0 , 0 ,,
    1.25    1.25
     200     216
    1.25    1.25
     200     216
Pier Skew, UpSta & Num, DnSta & Num=,630, 2 ,630, 2 , 0 , 0 , 0 ,,
    1.25    1.25
     200     216
    1.25    1.25
     200     216
Pier Skew, UpSta & Num, DnSta & Num=,980, 2 ,980, 2 , 0 , 0 , 0 ,,
    1.25    1.25
     200     216
    1.25    1.25
     200     216
Pier Skew, UpSta & Num, DnSta & Num=,1000, 2 ,1000, 2 , 0 , 0 , 0 ,,
    1.25    1.25
     200     216
    1.25    1.25
     200     216
Pier Skew, UpSta & Num, DnSta & Num=,1020, 2 ,1020, 2 , 0 , 0 , 0 ,,
    1.25    1.25
     200     216
    1.25    1.25
     200     216
Pier Skew, UpSta & Num, DnSta & Num=,1040, 2 ,1040, 2 , 0 , 0 , 0 ,,
    1.25    1.25
     200     216
    1.25    1.25
     200     216
Pier Skew, UpSta & Num, DnSta & Num=,1060, 2 ,1060, 2 , 0 , 0 , 0 ,,
    1.25    1.25
     200     216
    1.25    1.25
     200     216
Pier Skew, UpSta & Num, DnSta & Num=,1080, 2 ,1080, 2 , 0 , 0 , 0 ,,
    1.25    1.25
     200     216
    1.25    1.25
     200     216
Pier Skew, UpSta & Num, DnSta & Num=,1100, 2 ,1100, 2 , 0 , 0 , 0 ,,
    1.25    1.25
     200     216
    1.25    1.25
     200     216
Pier Skew, UpSta & Num, DnSta & Num=,1120, 2 ,1120, 2 , 0 , 0 , 0 ,,
    1.25    1.25
     200     216
    1.25    1.25
     200     216
Pier Skew, UpSta & Num, DnSta & Num=,1140, 2 ,1140, 2 , 0 , 0 , 0 ,,
    1.25    1.25
     200     216
    1.25    1.25
     200     216
Pier Skew, UpSta & Num, DnSta & Num=,1160, 2 ,1160, 2 , 0 , 0 , 0 ,,
    1.25    1.25
     200     216
    1.25    1.25
     200     216
Pier Skew, UpSta & Num, DnSta & Num=,1180, 2 ,1180, 2 , 0 , 0 , 0 ,,
    1.25    1.25
     200     216
    1.25    1.25
     200     216
Pier Skew, UpSta & Num, DnSta & Num=,1200, 2 ,1200, 2 , 0 , 0 , 0 ,,
    1.25    1.25
     200     216
    1.25    1.25
     200     216
Pier Skew, UpSta & Num, DnSta & Num=,1220, 2 ,1220, 2 , 0 , 0 , 0 ,,
    1.25    1.25
     200     216
    1.25    1.25
     200     216
BR Coef=-1 ,-1 ,-1 ,1.25, 0 ,,.34,.8,0,2,0,
WSPro=,,,, 1 ,,,, 0 ,,,, 0 ,,,,-1 ,-1 ,-1 , 0 , 0 , 0 , 0 , 0
BR Coef=-1 , 0 , 0 ,1.25, 0 ,,.34,.8,0,2,1,
WSPro=,,,, 1 ,,,, 0 ,,,, 0 ,,,,-1 ,-1 ,-1 , 0 , 0 , 0 , 0 , 0
Multiple Barrel Culv=2,4,6,60,.013,.4,1,8,1,211.7,211.6, 5,Culvert #1  , 0 ,30
     200     200     220     220     240     240     260     260     280     280
BC Mult= 2 ,0,390,0,390
BC Mult= 3 ,310,880,310,880
BC Mult= 3 ,700,1850,700,1850
BC Design=,, 0 ,, 0 ,,,,,,

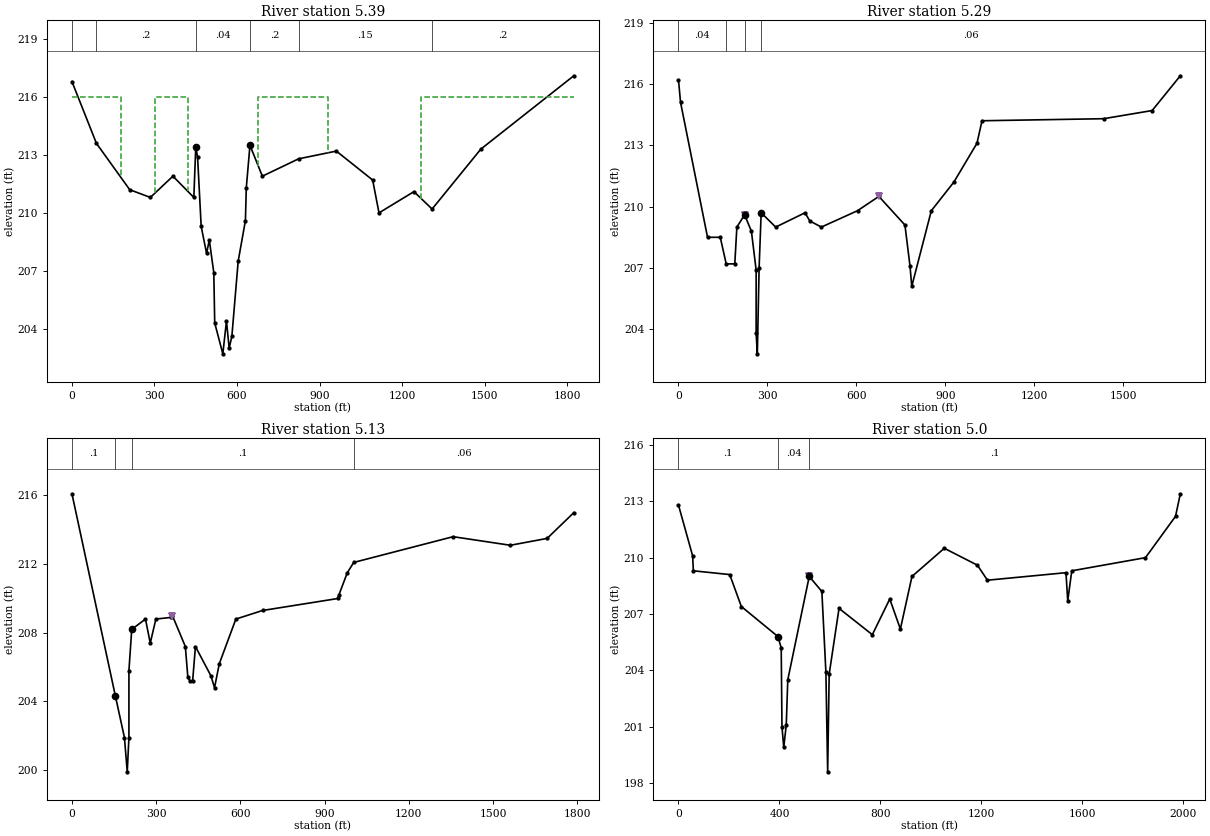
Type RM Length L Ch R = 1 ,5.39    ,320,500,580
BEGIN DESCRIPTION:
downstream of bridge embankment
END DESCRIPTION:
#Sta/Elev= 30
       0   216.8      89   213.6     210   211.2     285   210.8     367   211.9
     443   210.8     450   213.4   456.6   212.9   469.7   209.3   489.4   207.9
   499.2   208.6   515.6   206.9   518.9   204.3   548.4   202.7   561.6   204.4
   571.4     203   581.2   203.6   604.2   207.5   630.5   209.6   633.7   211.3
     647   213.5     692   211.9     824   212.8     961   213.2    1093   211.7
    1116     210    1243   211.1    1309   210.2    1486   213.3    1824   217.1
#Mann= 6 , 1 , 0
       0     .15       0      89      .2       0     450     .04       0
     647      .2       0     824     .15       0    1309      .2       0
#XS Ineff= 4 ,-1
       0     177     216     303     420     216     677     930     216
    1270    1850     216
Bank Sta=450,647
Exp/Cntr=.5,.3

Type RM Length L Ch R = 1 ,5.29    ,410,416.5,410
BEGIN DESCRIPTION:
River Station 5.29
END DESCRIPTION:
#Sta/Elev= 30
       0   216.2       7   215.1      98   208.5     141   208.5     161   207.2
     190   207.2     197     209     223   209.6     246   208.8     262   206.9
     262   203.8     266   202.8     272     207     279   209.7     328     209
     427   209.7     443   209.3     482     209     604   209.8     676   210.5
     764   209.1     781   207.1     787   206.1     853   209.8     929   211.2
    1007   213.1    1024   214.2    1434   214.3    1598   214.7    1693   216.4
#Mann= 4 , 1 , 0
       0     .04       0     161     .06       0     223     .04       0
     279     .06       0
Levee=-1,223,209.6,-1,676,210.5
Bank Sta=223,279
Exp/Cntr=.3,.1

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
Type RM Length L Ch R = 1 ,5.13    ,310,355,340
BEGIN DESCRIPTION:
River Station 5.13
END DESCRIPTION:
#Sta/Elev= 30
       0   216.1     155   204.3     187   201.9     197   199.9     203   201.9
     203   205.8     213   208.2     262   208.8     279   207.4     299   208.8
     354   208.9     358     209     404   207.2     413   205.4     420   205.2
     430   205.2     440   207.2     495   205.5     508   204.8     525   206.2
     584   208.8     679   209.3     948     210     951   210.2     981   211.5
    1004   212.1    1358   213.6    1562   213.1    1693   213.5    1788     215
#Mann= 4 , 1 , 0
       0      .1       0     155     .04       0     213      .1       0
    1004     .06       0
Levee=0,,,-1,358,209
Bank Sta=155,213
Exp/Cntr=.3,.1

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
Type RM Length L Ch R = 1 ,5.0     ,0,0,0
BEGIN DESCRIPTION:
Downstream Boundary Section
END DESCRIPTION:
#Sta/Elev= 30
       0   212.8      56   210.1      59   209.3     203   209.1     249   207.4
     394   205.8     407   205.2     410     201     417   199.9     427   201.1
     433   203.5     518     209     568   208.2     584   203.9     591   198.6
     597   203.8     636   207.3     768   205.9     837   207.8     879   206.2
     925     209    1053   210.5    1184   209.6    1224   208.8    1535   209.2
    1542   207.7    1558   209.3    1850     210    1969   212.2    1988   213.4
#Mann= 3 , 0 , 0
       0      .1       0     394     .04       0     518      .1       0
Levee=0,,,-1,518,209
Bank Sta=394,518
Exp/Cntr=.3,.1

Chan Stop Cuts=-1

--- Wrk4_sol.g01 (geometry) ---

Geom Title=Beaver Cr. + Bridge - P/W

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
River Reach=Beaver Creek    ,Beaver Creek

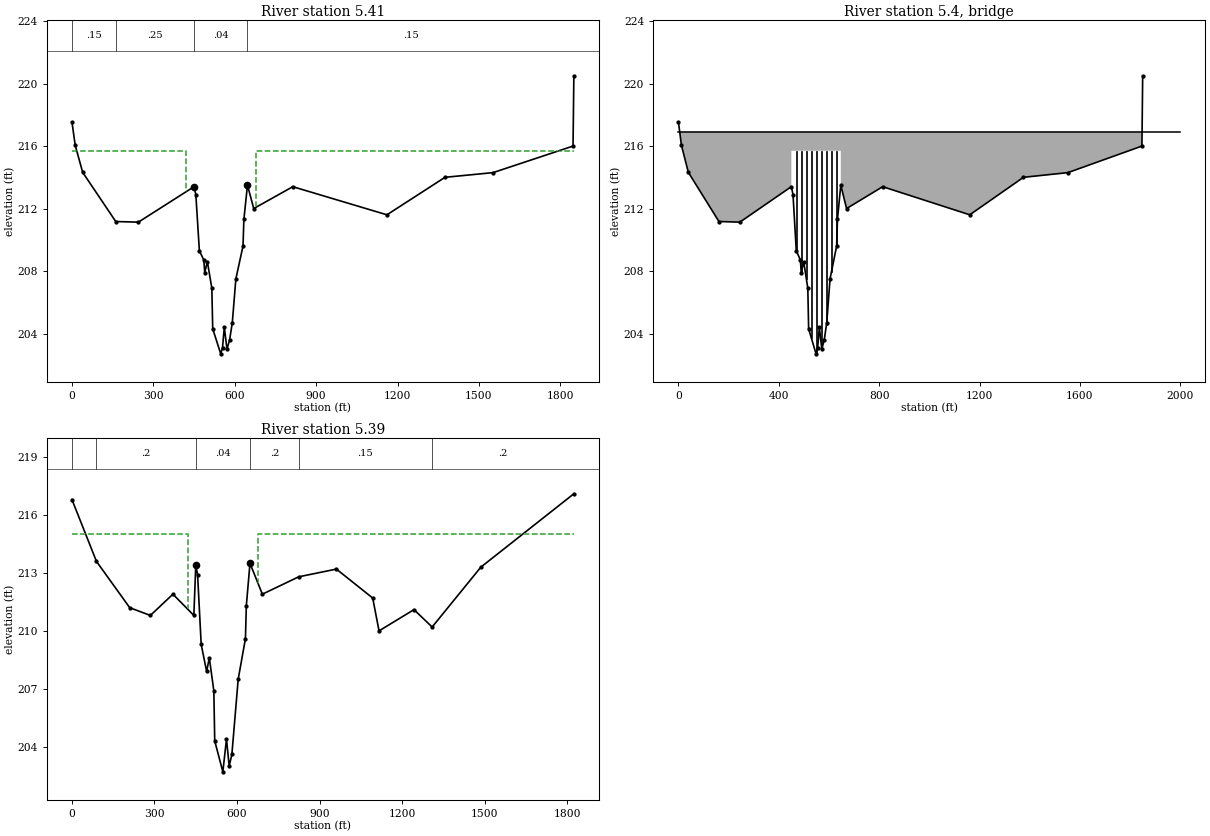
Type RM Length L Ch R = 1 ,5.41    ,100,100,100
BEGIN DESCRIPTION:
upstream of bridge embankment
END DESCRIPTION:
#Sta/Elev= 30
       0  217.55      12  216.05    39.5  214.32   161.5  211.17   244.8  211.13
     450   213.4   456.6   212.9   469.7   209.3   486.1   208.7   489.4   207.9
   499.2   208.6   515.6   206.9   518.9   204.3   548.4   202.7     555   203.1
   561.6   204.4   571.4     203   581.2   203.6   591.1   204.7   604.2   207.5
   630.5   209.6   633.7   211.3     647   213.5     670     212     814   213.4
    1161   211.6    1375     214    1552   214.3    1847     216    1850   220.5
#Mann= 4 , 1 , 0
       0     .15       0   161.5     .25       0     450     .04       0
     647     .15       0
#XS Ineff= 2 , 0
             420   215.7     677           215.7
Bank Sta=450,647
Exp/Cntr=.5,.3

Type RM Length L Ch R = 3 ,5.4     ,,,
BEGIN DESCRIPTION:
Bridge # 1
END DESCRIPTION:
Bridge Culvert--1,-1,-1,-1
Deck Dist Width WeirC Skew NumUp NumDn MinLoCord MaxHiCord MaxSubmerge Is_Ogee
30,40,2.6,,6,6,,,.95,0,2,2,,
       0     450     450     647     647    2000
  216.93  216.93  216.93  216.93  216.93  216.93
     200     200   215.7   215.7     200     200
       0     450     450     647     647    2000
  216.93  216.93  216.93  216.93  216.93  216.93
     200     200   215.7   215.7     200     200
Pier Skew, UpSta & Num, DnSta & Num=,470, 2 ,470, 2 , 0 , 0 , 0 ,,
    1.25    1.25
     200     216
    1.25    1.25
     200     216
Pier Skew, UpSta & Num, DnSta & Num=,490, 2 ,490, 2 , 0 , 0 , 0 ,,
    1.25    1.25
     200     216
    1.25    1.25
     200     216
Pier Skew, UpSta & Num, DnSta & Num=,510, 2 ,510, 2 , 0 , 0 , 0 ,,
    1.25    1.25
     200     216
    1.25    1.25
     200     216
Pier Skew, UpSta & Num, DnSta & Num=,530, 2 ,530, 2 , 0 , 0 , 0 ,,
    1.25    1.25
     200     216
    1.25    1.25
     200     216
Pier Skew, UpSta & Num, DnSta & Num=,550, 2 ,550, 2 , 0 , 0 , 0 ,,
    1.25    1.25
     200     216
    1.25    1.25
     200     216
Pier Skew, UpSta & Num, DnSta & Num=,570, 2 ,570, 2 , 0 , 0 , 0 ,,
    1.25    1.25
     200     216
    1.25    1.25
     200     216
Pier Skew, UpSta & Num, DnSta & Num=,590, 2 ,590, 2 , 0 , 0 , 0 ,,
    1.25    1.25
     200     216
    1.25    1.25
     200     216
Pier Skew, UpSta & Num, DnSta & Num=,610, 2 ,610, 2 , 0 , 0 , 0 ,,
    1.25    1.25
     200     216
    1.25    1.25
     200     216
Pier Skew, UpSta & Num, DnSta & Num=,630, 2 ,630, 2 , 0 , 0 , 0 ,,
    1.25    1.25
     200     216
    1.25    1.25
     200     216
BR Coef= 1 , 0 , 0 ,1.25, 0 ,,.34,.8,0,2,0,
WSPro=,,,, 1 ,,,, 0 ,,,, 0 ,,,,-1 ,-1 ,-1 , 0 , 0 , 0 , 0 , 0
BR Coef= 1 , 0 , 0 ,1.25, 0 ,,.34,.8,0,2,1,
WSPro=,,,, 1 ,,,, 0 ,,,, 0 ,,,,-1 ,-1 ,-1 , 0 , 0 , 0 , 0 , 0
BC Design=,, 0 ,, 0 ,,,,,,

Type RM Length L Ch R = 1 ,5.39    ,320,500,580
BEGIN DESCRIPTION:
downstream of bridge embankment
END DESCRIPTION:
#Sta/Elev= 30
       0   216.8      89   213.6     210   211.2     285   210.8     367   211.9
     443   210.8     450   213.4   456.6   212.9   469.7   209.3   489.4   207.9
   499.2   208.6   515.6   206.9   518.9   204.3   548.4   202.7   561.6   204.4
   571.4     203   581.2   203.6   604.2   207.5   630.5   209.6   633.7   211.3
     647   213.5     692   211.9     824   212.8     961   213.2    1093   211.7
    1116     210    1243   211.1    1309   210.2    1486   213.3    1824   217.1
#Mann= 6 , 1 , 0
       0     .15       0      89      .2       0     450     .04       0
     647      .2       0     824     .15       0    1309      .2       0
#XS Ineff= 2 , 0
             420     215     677             215
Bank Sta=450,647
Exp/Cntr=.5,.3