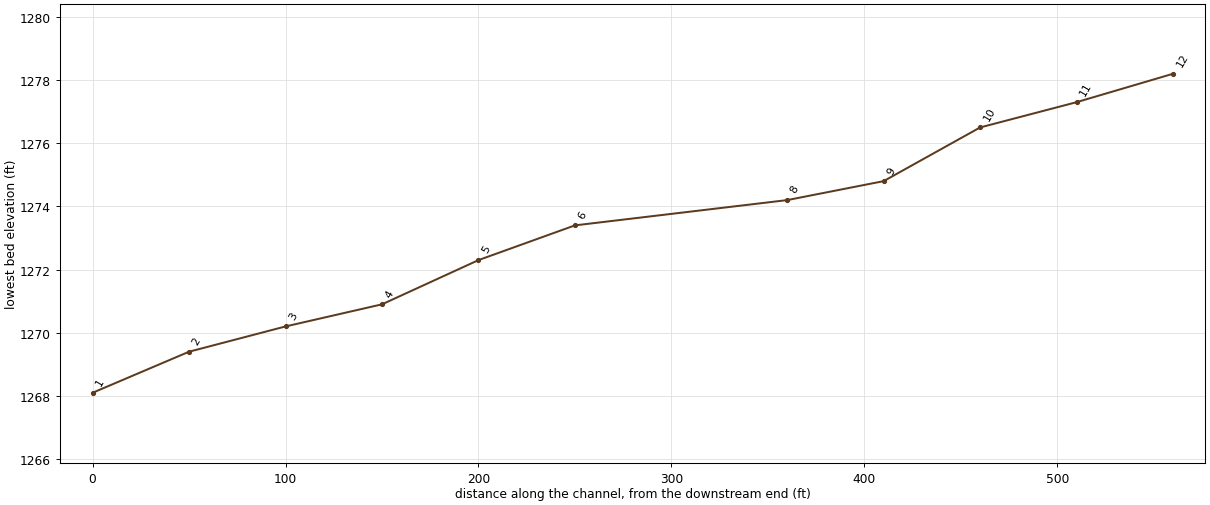
--- Wrk5_sol.prj (project) ---

Proj Title=Mixed Flow Workshop - Solutions
Current Plan=p03
Default Exp/Contr=.3,.1
English Units
Geom File=g02
Geom File=g01
Flow File=f01
Plan File=p04
Plan File=p03
Plan File=p01
Plan File=p02
BEGIN DESCRIPTION:
END DESCRIPTION:

--- Wrk5_sol.p03 (plan) ---

Plan Title=Putah Creek Bridge - Energy + Mix
Short Identifier=Energy+Mix
Geom File=g01
Flow File=f01
Interactive Comp Mode
Mixed Flow
K Sum by GR= 0
Std Step Tol= 0.01
Critical Tol= 0.01
Num of Std Step Trials= 20
Max Error Tol= 0.3
Flow Tol Ratio= 0.001
Log Output Level= 0
Friction Slope Method= 1
Calc Critical at every XS
Parabolic Critical Depth
Global Vel Dist= 0 , 0 , 0
Global Log Level= 0
Encroach Param=-1 ,0,0, 0

--- Wrk5_sol.p01 (plan) ---

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Plan Title=Putah Creek Bridge - Energy + Sub
Short Identifier=Energy+Sub
Geom File=g01
Flow File=f01
Multiple Comp Mode
Subcritical Flow
Std Step Tol= .01
Critical Tol= .01
Max Error Tol= .3
Flow Tol Ratio= .001

--- Wrk5_sol.p02 (plan) ---

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Plan Title=Putah Creek Bridge - Energy + Sup
Short Identifier=Energy+Sup
Geom File=g01
Flow File=f01
Multiple Comp Mode
Supercritical Flow
Std Step Tol= .01
Critical Tol= .01
Max Error Tol= .3
Flow Tol Ratio= .001

--- Wrk5_sol.p04 (plan) ---

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Plan Title=Putah Creek Bridge - P/W + Mix
Short Identifier=P/W+Mix
Geom File=g02
Flow File=f01
Multiple Comp Mode
Std Step Tol= .01
Critical Tol= .01
Max Error Tol= .3
Flow Tol Ratio= .001

--- Wrk5_sol.f01 (steady flow) ---

Flow Title=100 Year Discharge
Number of Profiles= 1
Profile Names=PF#1
River Rch & RM=Putah Creek,Davis           ,12
    3200
Boundary for River Rch & Prof#=Putah Creek,Davis           , 1
Up Type= 3
Up Slope=0.01
Dn Type= 2

--- Wrk5_sol.g01 (geometry) ---

Geom Title=Base Geometry Data - Energy

River Reach=Putah Creek     ,Davis
Reach XY= 23
        .1903873        .8772688        .2375238        .8643457
        .2789917         .822065        .2999122        .7952996
         .313449        .7785711        .3331389        .7568242
        .3466757        .7250402        .3737492        .6798735
        .3885166        .6347067        .4094371        .5828486
        .4192821        .5460461        .4352801        .5025522
        .4463556        .4590583        .4623537        .4239286
              .5        .3908642        .5361907         .367052
        .5632643        .3386137        .5841848        .3118482
        .6051052        .2850828         .618642        .2482802
        .6272564        .2131506        .6358707        .1780209
        .6407931        .1428912

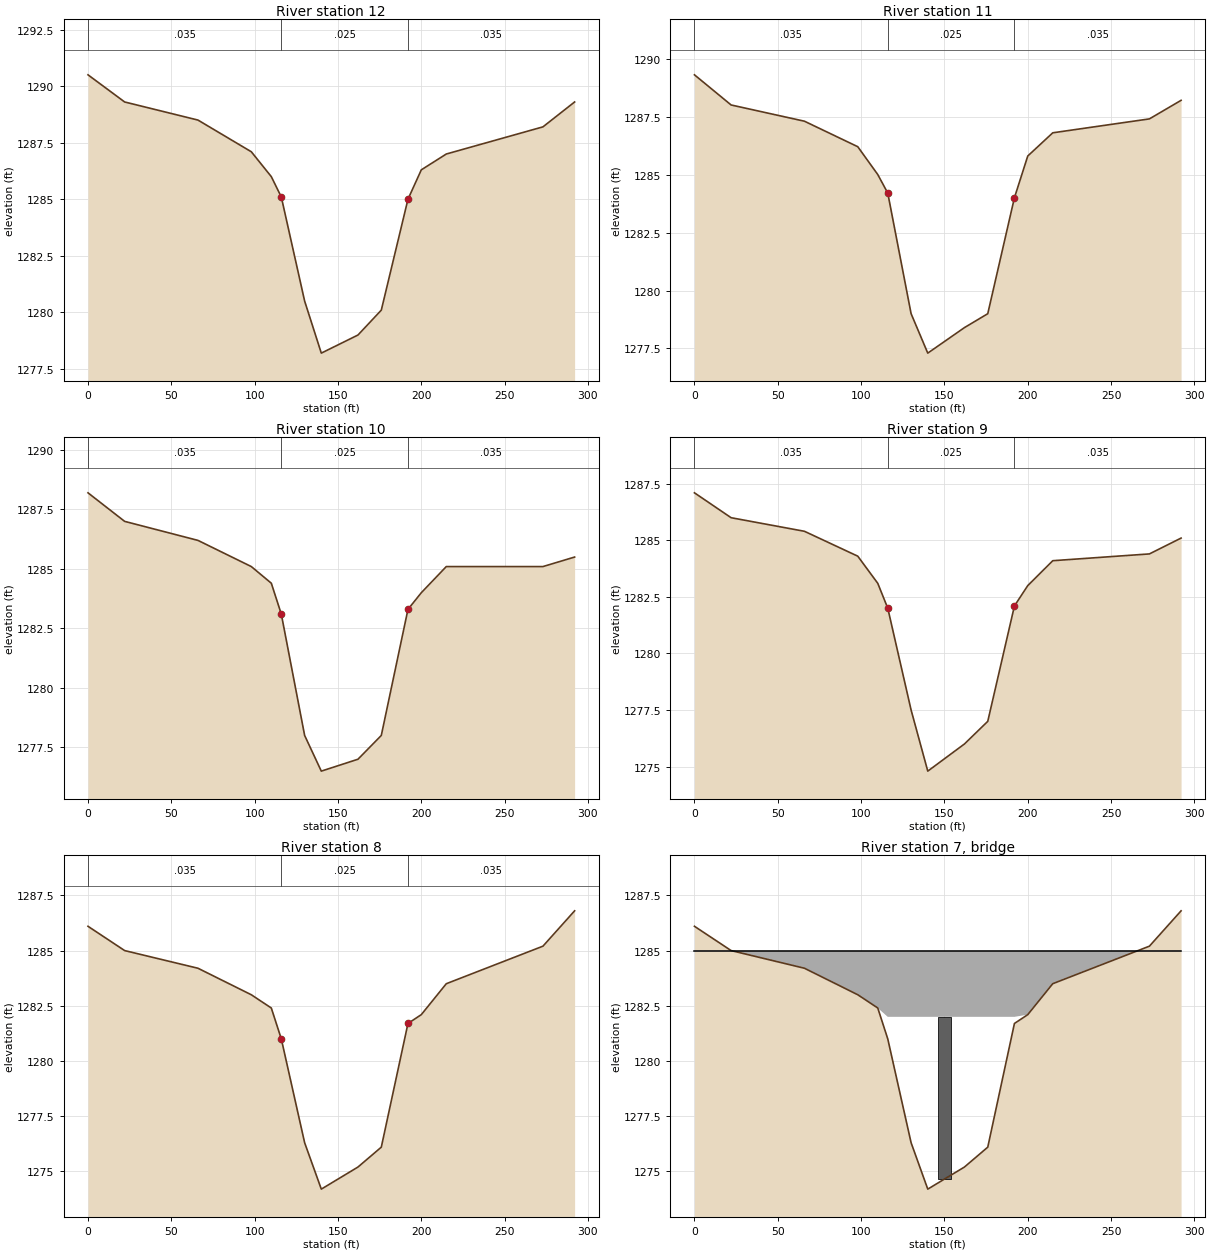
Type RM Length L Ch R = 1 ,12      ,47.5,50,60
BEGIN DESCRIPTION:
Upstream River Station 12
END DESCRIPTION:
#Sta/Elev= 15
       0  1290.5      22  1289.3      66  1288.5      98  1287.1     110    1286
     116  1285.1     130  1280.5     140  1278.2     162    1279     176  1280.1
     192    1285     200  1286.3     215    1287     273  1288.2     292  1289.3
#Mann= 3 , 0 , 0
       0    .035       0     116    .025       0     192    .035       0
Bank Sta=116,192
Exp/Cntr=0.1,0.1

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
Type RM Length L Ch R = 1 ,11      ,62.5,50,45
BEGIN DESCRIPTION:
Cross Section 11
END DESCRIPTION:
#Sta/Elev= 15
       0  1289.3      22    1288      66  1287.3      98  1286.2     110    1285
     116  1284.2     130    1279     140  1277.3     162  1278.4     176    1279
     192    1284     200  1285.8     215  1286.8     273  1287.4     292  1288.2
#Mann= 3 , 0 , 0
       0    .035       0     116    .025       0     192    .035       0
Bank Sta=116,192
Exp/Cntr=0.1,0.1

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
Type RM Length L Ch R = 1 ,10      ,47.5,50,51.5
BEGIN DESCRIPTION:
Cross Section 10
END DESCRIPTION:
#Sta/Elev= 15
       0  1288.2      22    1287      66  1286.2      98  1285.1     110  1284.4
     116  1283.1     130    1278     140  1276.5     162    1277     176    1278
     192  1283.3     200    1284     215  1285.1     273  1285.1     292  1285.5
#Mann= 3 , 0 , 0
       0    .035       0     116    .025       0     192    .035       0
Bank Sta=116,192
Exp/Cntr=0.1,0.1

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
Type RM Length L Ch R = 1 ,9       ,60.5,50,50
BEGIN DESCRIPTION:
Cross Section 9
END DESCRIPTION:
#Sta/Elev= 15
       0  1287.1      22    1286      66  1285.4      98  1284.3     110  1283.1
     116    1282     130  1277.5     140  1274.8     162    1276     176    1277
     192  1282.1     200    1283     215  1284.1     273  1284.4     292  1285.1
#Mann= 3 , 0 , 0
       0    .035       0     116    .025       0     192    .035       0
Bank Sta=116,192
Exp/Cntr=0.3,0.1

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
Type RM Length L Ch R = 1 ,8       ,110,110,110
BEGIN DESCRIPTION:
Cross Section 8
END DESCRIPTION:
#Sta/Elev= 15
       0  1286.1      22    1285      66  1284.2      98    1283     110  1282.4
     116    1281     130  1276.3     140  1274.2     162  1275.2     176  1276.1
     192  1281.7     200  1282.1     215  1283.5     273  1285.2     292  1286.8
#Mann= 3 , 0 , 0
       0    .035       0     116    .025       0     192    .035       0
Bank Sta=116,192
Exp/Cntr=0.3,0.1

Type RM Length L Ch R = 3 ,7       ,,,
BEGIN DESCRIPTION:
Large Pier Bridge
END DESCRIPTION:
Bridge Culvert--1,-1,-1,-1
Deck Dist Width WeirC Skew NumUp NumDn MinLoCord MaxHiCord MaxSubmerge Is_Ogee
10,90,2.5999999,,2,2,,,0.95,0,,,,
       0     292
    1285    1285
    1282    1282
       0     292
    1285    1285
    1282    1282
Pier Skew, UpSta & Num, DnSta & Num=,150, 2 ,150, 2 , 0 , 0
       8       8
    1272    1284
       8       8
    1272    1284
BR Coef= 1 ,-1 , 0 ,, 0 ,,,,-1,1.33,0,
WSPro=,,,, 1 ,,,, 0 ,,,, 0 ,,,,-1 ,-1 ,-1 , 0 , 0 , 0 , 0 , 0

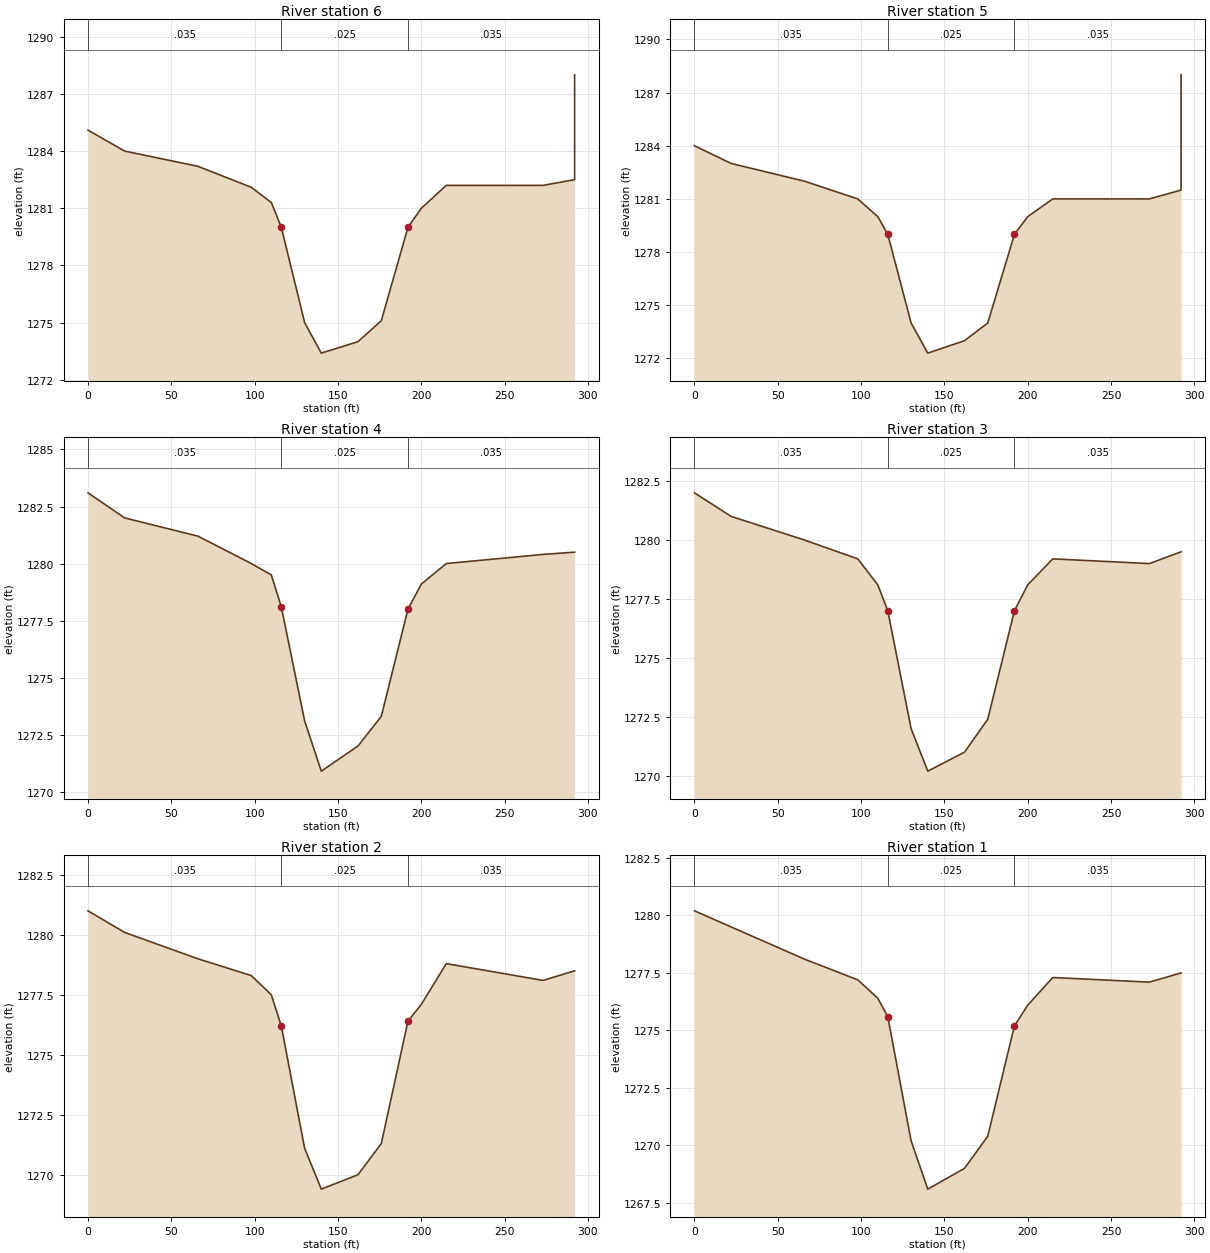
Type RM Length L Ch R = 1 ,6       ,52.5,50,47.5
BEGIN DESCRIPTION:
Cross Section 6
END DESCRIPTION:
#Sta/Elev= 16
       0  1285.1      22    1284      66  1283.2      98  1282.1     110  1281.3
     116    1280     130    1275     140  1273.4     162    1274     176  1275.1
     192    1280     200    1281     215  1282.2     273  1282.2     292  1282.5
     292    1288
#Mann= 3 , 0 , 0
       0    .035       0     116    .025       0     192    .035       0
Bank Sta=116,192
Exp/Cntr=0.1,0.1

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
Type RM Length L Ch R = 1 ,5       ,62,50,47.5
BEGIN DESCRIPTION:
Cross Section 5
END DESCRIPTION:
#Sta/Elev= 16
       0    1284      22    1283      66    1282      98    1281     110    1280
     116    1279     130    1274     140  1272.3     162    1273     176    1274
     192    1279     200    1280     215    1281     273    1281     292  1281.5
     292    1288
#Mann= 3 , 0 , 0
       0    .035       0     116    .025       0     192    .035       0
Bank Sta=116,192
Exp/Cntr=0.1,0.1

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
Type RM Length L Ch R = 1 ,4       ,50,50,50
BEGIN DESCRIPTION:
Cross Section 4
END DESCRIPTION:
#Sta/Elev= 15
       0  1283.1      22    1282      66  1281.2      98    1280     110  1279.5
     116  1278.1     130  1273.1     140  1270.9     162    1272     176  1273.3
     192    1278     200  1279.1     215    1280     273  1280.4     292  1280.5
#Mann= 3 , 0 , 0
       0    .035       0     116    .025       0     192    .035       0
Bank Sta=116,192
Exp/Cntr=0.1,0.1

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
Type RM Length L Ch R = 1 ,3       ,55,50,45
BEGIN DESCRIPTION:
Cross Section 3
END DESCRIPTION:
#Sta/Elev= 15
       0    1282      22    1281      66    1280      98  1279.2     110  1278.1
     116    1277     130    1272     140  1270.2     162    1271     176  1272.4
     192    1277     200  1278.1     215  1279.2     273    1279     292  1279.5
#Mann= 3 , 0 , 0
       0    .035       0     116    .025       0     192    .035       0
Bank Sta=116,192
Exp/Cntr=0.1,0.1

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
Type RM Length L Ch R = 1 ,2       ,60,50,45
BEGIN DESCRIPTION:
Cross Section 2
END DESCRIPTION:
#Sta/Elev= 15
       0    1281      22  1280.1      66    1279      98  1278.3     110  1277.5
     116  1276.2     130  1271.1     140  1269.4     162    1270     176  1271.3
     192  1276.4     200  1277.1     215  1278.8     273  1278.1     292  1278.5
#Mann= 3 , 0 , 0
       0    .035       0     116    .025       0     192    .035       0
Bank Sta=116,192
Exp/Cntr=0.1,0.1

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
Type RM Length L Ch R = 1 ,1       ,0,0,0
BEGIN DESCRIPTION:
Downstream River Station 1
END DESCRIPTION:
#Sta/Elev= 15
       0  1280.2      22  1279.5      66  1278.1      98  1277.2     110  1276.4
     116  1275.6     130  1270.2     140  1268.1     162    1269     176  1270.4
     192  1275.2     200  1276.1     215  1277.3     273  1277.1     292  1277.5
#Mann= 3 , 0 , 0
       0    .035       0     116    .025       0     192    .035       0
Bank Sta=116,192
Exp/Cntr=0.1,0.1

Chan Stop Cuts=-1

--- Wrk5_sol.g02 (geometry) ---

Geom Title=Base Geometry Data - Press/Weir

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
River Reach=Putah Creek     ,Davis

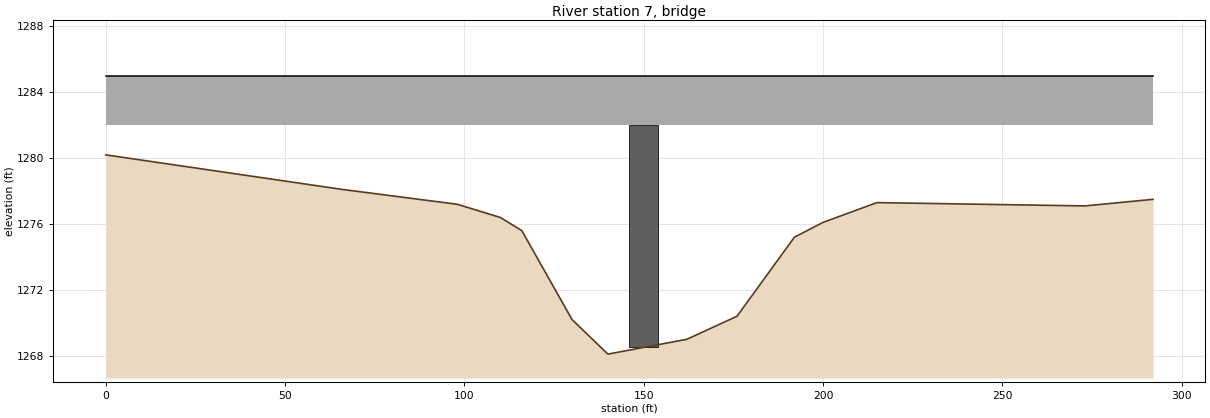
Type RM Length L Ch R = 3 ,7       ,,,
BEGIN DESCRIPTION:
Large Pier Bridge
END DESCRIPTION:
Bridge Culvert--1,-1,-1,-1
Deck Dist Width WeirC Skew NumUp NumDn MinLoCord MaxHiCord MaxSubmerge Is_Ogee
10,90,2.5999999,,2,2,,,0.95,0,,,,
       0     292
    1285    1285
    1282    1282
       0     292
    1285    1285
    1282    1282
Pier Skew, UpSta & Num, DnSta & Num=,150, 2 ,150, 2 , 0 , 0
       8       8
    1272    1284
       8       8
    1272    1284
BR Coef= 1 ,-1 , 0 ,, 0 ,,,0.8,0,1.33,0,
WSPro=,,,, 1 ,,,, 0 ,,,, 0 ,,,,-1 ,-1 ,-1 , 0 , 0 , 0 , 0 , 0