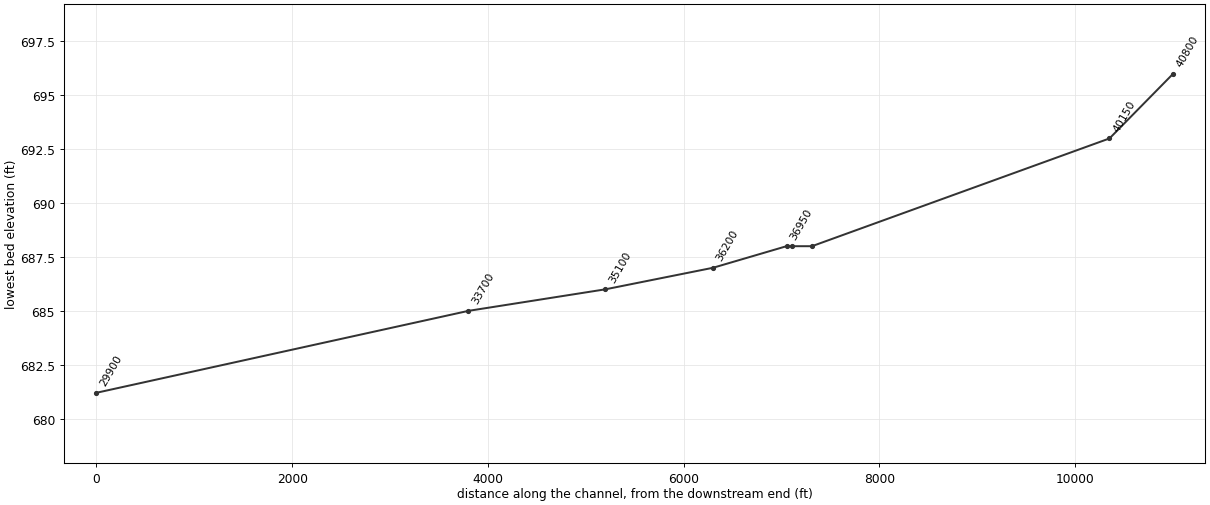
--- Wrk6_sol.prj (project) ---

Proj Title=Buffalo Ck. Import
Current Plan=p02
Default Exp/Contr=.3,.1
English Units
Geom File=g02
Geom File=g01
Geom File=g02
Flow File=f02
Flow File=f03
Flow File=f01
Flow File=f02
Flow File=f03
Flow File=f02
Flow File=f01
Plan File=p03
Plan File=p05
Plan File=p02
BEGIN DESCRIPTION:
END DESCRIPTION:

--- Wrk6_sol.p02 (plan) ---

Plan Title=Buffalo Ck. Existing
Short Identifier=Base flood
Geom File=g02
Flow File=f01
Multiple Comp Mode
Subcritical Flow
K Sum by GR= 0
Std Step Tol= .01
Critical Tol= .01
Num of Std Step Trials= 20
Max Error Tol= .3
Flow Tol Ratio= .001
Log Output Level= 0
Friction Slope Method= 1
Parabolic Critical Depth

--- Wrk6_sol.p01 (plan) ---

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Plan Title=Imported Plan 01
Short Identifier=Imported Pla
Geom File=g01
Flow File=f01

--- Wrk6_sol.p03 (plan) ---

Plan Title=Floodway Trial 1
Short Identifier=floodway 2
Geom File=g02
Flow File=f02
Interactive Comp Mode
Subcritical Flow
K Sum by GR= 0
Std Step Tol= 0.01
Critical Tol= 0.01
Num of Std Step Trials= 20
Max Error Tol= 0.3
Flow Tol Ratio= 0.001
Log Output Level= 0
Friction Slope Method= 1
Parabolic Critical Depth
Global Vel Dist= 0 , 0 , 0
Global Log Level= 0
Encroach Param=-1 ,0,0, 4
Encroach River=1
Encroach Reach=1
Encroach Node=40800
       4      .8               4       1               5       1       1
Encroach Node=40150
       4      .8               4       1               5       1       1
Encroach Node=37200
       4      .8               4       1               5       1       1
Encroach Node=37000
       4      .8               4       1               5       1       1
Encroach Node=36975
       4      .8               4       1               5       1       1
Encroach Node=36950
       4      .8               4       1               5       1       1
Encroach Node=36200
       4      .8               4       1               5       1       1
Encroach Node=35100
       4      .8               4       1               5       1       1
Encroach Node=33700
       4      .8               4       1               5       1       1
Encroach Node=29900
       4      .8               4       1               5       1       1

--- Wrk6_sol.p05 (plan) ---

Plan Title=Floodway Trial 2
Short Identifier=floodway 2
Geom File=g02
Flow File=f03
Interactive Comp Mode
Subcritical Flow
K Sum by GR= 0
Std Step Tol= 0.01
Critical Tol= 0.01
Num of Std Step Trials= 20
Max Error Tol= 0.3
Flow Tol Ratio= 0.001
Log Output Level= 0
Friction Slope Method= 1
Parabolic Critical Depth
Global Vel Dist= 0 , 0 , 0
Global Log Level= 0
Encroach Param=-1 ,0,0, 2
Encroach River=1
Encroach Reach=1
Encroach Node=40800
       1    94.5     232
Encroach Node=40150
       1    94.7     229
Encroach Node=37200
       1     109     325
Encroach Node=37000
       1     115     321
Encroach Node=36975
       1  119.27   305.7
Encroach Node=36950
       1  119.27   305.7
Encroach Node=36200
       1     176     377
Encroach Node=35100
       1   114.7     340
Encroach Node=33700
       1  114.68  441.73
Encroach Node=29900
       1   185.6     508

--- Wrk6_sol.f01 (steady flow) ---

Flow Title=Imported Flow 01
Number of Flows and Profiles and Boundary= 1, 1, 1
Rch & RM=1           ,40800
    8000
Boundary for Rch & Prof#=1           , 1
Up Type= 0
Up Value=0
Dn Type= 1
Dn Value=698.3

--- Wrk6_sol.f02 (steady flow) ---

Flow Title=Floodway 1% Flows
Number of Flows and Profiles and Boundary= 1, 4, 1
Rch & RM=1           ,40800
    8000    8000    8000    8000
Boundary for Rch & Prof#=1           , 1
Up Type= 32767
Up Value=0
Dn Type= 1
Dn Value=698.3
Boundary for Rch & Prof#=1           , 2
Up Type= 32767
Up Value=0
Dn Type= 1
Dn Value=699.3
Boundary for Rch & Prof#=1           , 3
Up Type= 32767
Up Value=0
Dn Type= 1
Dn Value=699.3
Boundary for Rch & Prof#=1           , 4
Up Type= 32767
Up Value=0
Dn Type= 1
Dn Value=699.3

--- Wrk6_sol.f03 (steady flow) ---

Flow Title=Floodway final flow
Number of Flows and Profiles and Boundary= 1, 2, 1
Rch & RM=1           ,40800
    8000    8000
Boundary for Rch & Prof#=1           , 1
Up Type= 32767
Up Value=0
Dn Type= 1
Dn Value=698.3
Boundary for Rch & Prof#=1           , 2
Up Type= 32767
Up Value=0
Dn Type= 1
Dn Value=699.3

--- Wrk6_sol.g02 (geometry) ---

Geom Title=Buffalo Base Model
ViewRect= 0, 1, 1, 0
Reach=1
Rch X Y Up & X Y Dn=0.5,0.9,0.5,0.1
Rch Arrow X Y Up & X Y Dn=0,0,0,0
Rch Type=0

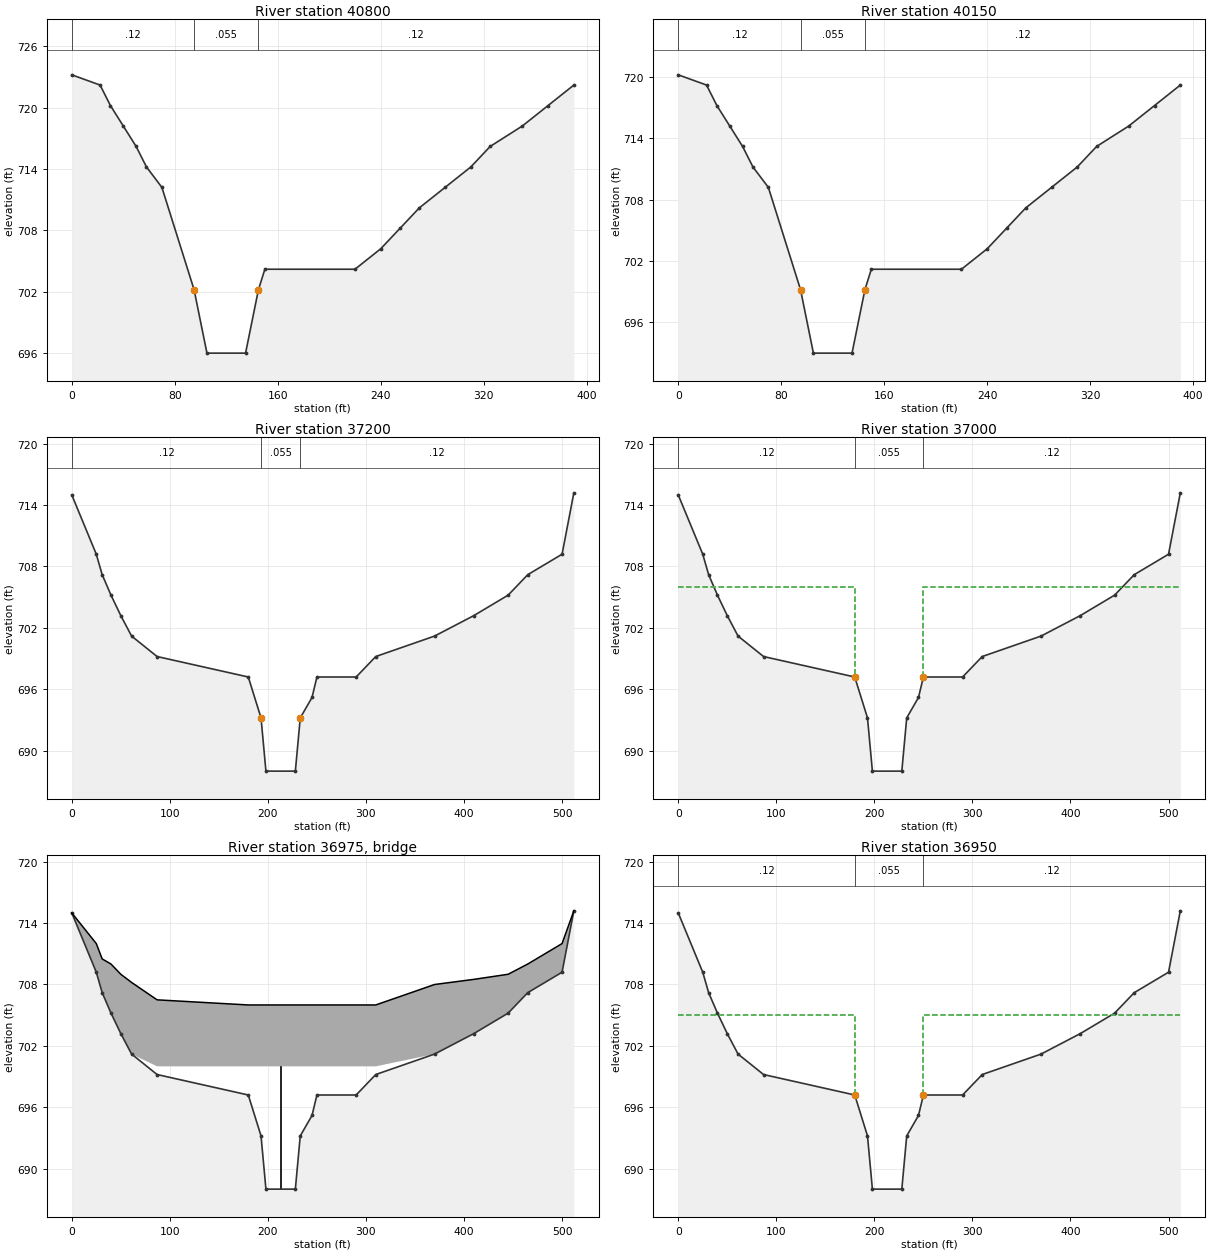
Type RM Length L Ch R =1,40800   ,650,650,650,0,0,0
Node Desc= 40800
#Sta/Elev= 22
       0   723.2      22   722.2      30   720.2      40   718.2      50   716.2
      58   714.2      70   712.2      95   702.2     105     696     135     696
     145   702.2     150   704.2     220   704.2     240   706.2     255   708.2
     270   710.2     290   712.2     310   714.2     325   716.2     350   718.2
     370   720.2     390   722.2
#Mann=3,0
       0     .12       1      95    .055       8     145     .12      11
Bank Sta=95,145
Exp/Cntr=0.3,0.1

Type RM Length L Ch R =1,40150   ,2800,3040,2800,0,0,0
Node Desc= 40150
#Sta/Elev= 22
       0   720.2      22   719.2      30   717.2      40   715.2      50   713.2
      58   711.2      70   709.2      95   699.2     105     693     135     693
     145   699.2     150   701.2     220   701.2     240   703.2     255   705.2
     270   707.2     290   709.2     310   711.2     325   713.2     350   715.2
     370   717.2     390   719.2
#Mann=3,0
       0     .12       1      95    .055       8     145     .12      11
Bank Sta=95,145
Exp/Cntr=0.3,0.1

Type RM Length L Ch R =1,37200   ,200,200,200,0,0,0
Node Desc= 37200
#Sta/Elev= 22
       0     715      25   709.2      31   707.2      40   705.2      50   703.2
      61   701.2      87   699.2     180   697.2     193   693.2     198     688
     228     688     233   693.2     245   695.2     250   697.2     290   697.2
     310   699.2     370   701.2     410   703.2     445   705.2     465   707.2
     500   709.2     512   715.2
#Mann=3,0
       0     .12       1     193    .055       9     233     .12      12
Bank Sta=193,233
Exp/Cntr=0.3,0.1

Type RM Length L Ch R =1,37000   ,60,60,60,0,0,0
Node Desc= 37000
#Sta/Elev= 22
       0     715      25   709.2      31   707.2      40   705.2      50   703.2
      61   701.2      87   699.2     180   697.2     193   693.2     198     688
     228     688     233   693.2     245   695.2     250   697.2     290   697.2
     310   699.2     370   701.2     410   703.2     445   705.2     465   707.2
     500   709.2     512   715.2
#Mann=3,0
       0     .12       0     180    .055       0     250     .12       0
#XS Ineff= 2 , 0
             180     706     250             706
Bank Sta=180,250
Exp/Cntr=0.3,0.1

Type RM Length L Ch R =3,36975   ,,,,0,0,0
Node Desc=Bridge # 1
Bridge Culvert--1,-1,-1,-1
Deck Dist Width WeirC Skew NumUp NumDn MinLoCord MaxHiCord MaxSubmerge Is_Ogee
5,50,2.9,,16,16,706,,0.95,0
       0      25      31      40      50      61      87     180     290     310
     370     410     445     465     500     512
     715     712   710.5     710     709   708.2   706.5     706     706     706
     708   708.5     709     710     712   715.2
     700     700     700     700     700     700     700     700     700     700
     700     700     700     700     700     700
       0      25      31      40      50      61      87     180     290     310
     370     410     445     465     500     512
     715     712   710.5     710     709   708.2   706.5     706     706     706
     708   708.5     709     710     712   715.2
     700     700     700     700     700     700     700     700     700     700
     700     700     700     700     700     700
Pier Skew, UpSta & Num, DnSta & Num=,213, 2,213, 2, 0, 0
     1.5     1.5
     688     704
     1.5     1.5
     688     704
Abutment Skew #Up #Dn=, 3, 3
      50     180     180
     700     700     600
      50     180     180
     700     700     600
Abutment Skew #Up #Dn=, 3, 3
     250     250     500
     600     700     700
     250     250     500
     600     700     700
BR Coef= 1, 0,-1,0.9, 0,,,0.8164966,0,2,2,700

Type RM Length L Ch R =1,36950   ,700,750,800,0,0,0
Node Desc= 36950
#Sta/Elev= 22
       0     715      25   709.2      31   707.2      40   705.2      50   703.2
      61   701.2      87   699.2     180   697.2     193   693.2     198     688
     228     688     233   693.2     245   695.2     250   697.2     290   697.2
     310   699.2     370   701.2     410   703.2     445   705.2     465   707.2
     500   709.2     512   715.2
#Mann=3,0
       0     .12       0     180    .055       0     250     .12       0
#XS Ineff= 2 , 0
             180     705     250             705
Bank Sta=180,250
Exp/Cntr=0.3,0.1

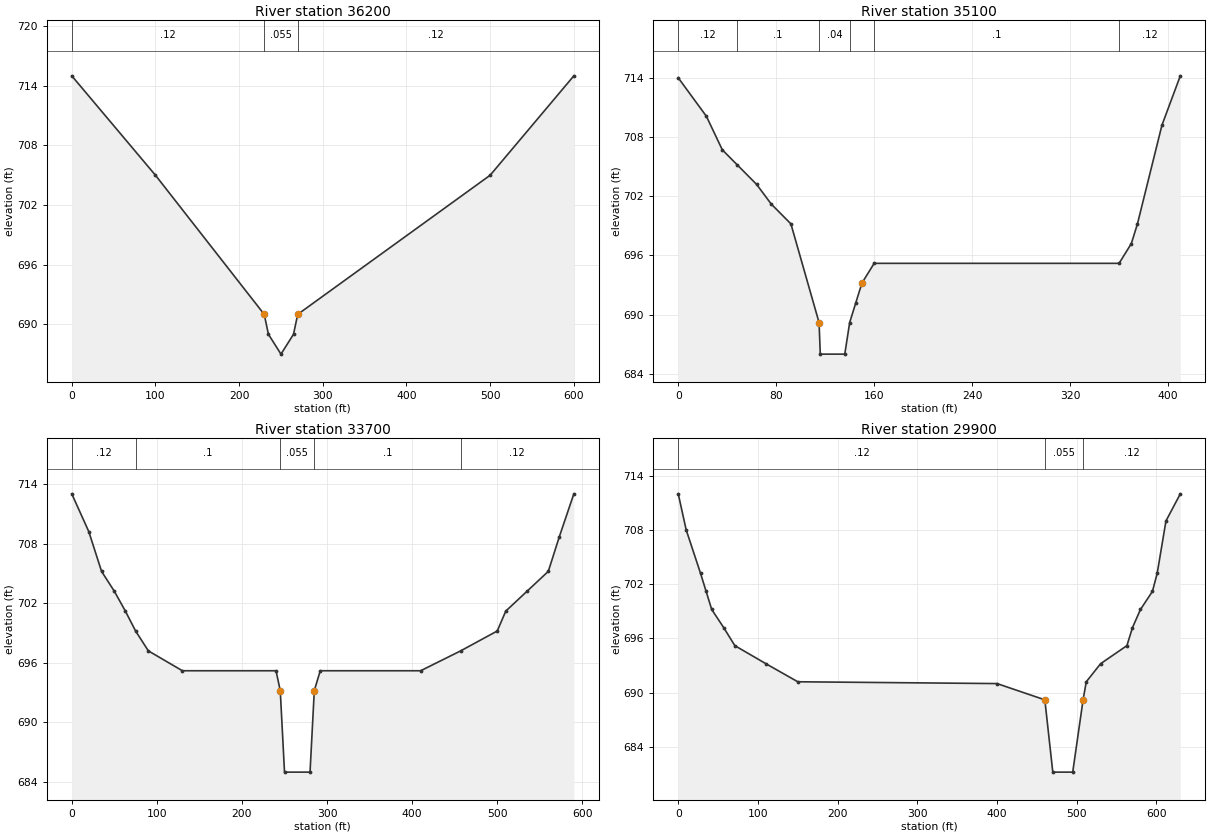
Type RM Length L Ch R =1,36200   ,1000,1100,1200,0,0,0
Node Desc= 36200
#Sta/Elev= 9
       0     715     100     705     230     691     235     689     250     687
     265     689     270     691     500     705     600     715
#Mann=3,0
       0     .12       1     230    .055       3     270     .12       7
Bank Sta=230,270
Exp/Cntr=0.3,0.1

Type RM Length L Ch R =1,35100   ,1000,1400,1500,0,0,0
Node Desc= 35100
#Sta/Elev= 19
       0     714      23   710.1      36   706.7      48   705.2      64   703.2
      76   701.2      92   699.2     115   689.2     116     686     136     686
     140   689.2     145   691.2     150   693.2     160   695.2     360   695.2
     370   697.2     375   699.2     395   709.2     410   714.2
#Mann=6,-1
       0     .12       1      48      .1       4     115     .04       8
     140     .06      11     160      .1      14     360     .12      15
Bank Sta=115,150
Exp/Cntr=0.3,0.1

Type RM Length L Ch R =1,33700   ,3000,3800,3000,0,0,0
Node Desc= 33700
#Sta/Elev= 22
       0     713      20   709.2      35   705.2      50   703.2      63   701.2
      75   699.2      90   697.2     130   695.2     240   695.2     245   693.2
     250     685     280     685     285   693.2     292   695.2     410   695.2
     457   697.2     500   699.2     510   701.2     535   703.2     560   705.2
     573   708.7     590     713
#Mann=5,-1
       0     .12       1      75      .1       6     245    .055      10
     285      .1      13     457     .12      16
Bank Sta=245,285
Exp/Cntr=0.3,0.1

Type RM Length L Ch R =1,29900   ,0,0,0,0,0,0
Node Desc= 29900
#Sta/Elev= 23
       0     712      10     708      28   703.2      35   701.2      42   699.2
      57   697.2      71   695.2     110   693.2     150   691.2     400     691
     460   689.2     470   681.2     495   681.2     508   689.2     512   691.2
     530   693.2     563   695.2     570   697.2     580   699.2     595   701.2
     601   703.2     612     709     630     712
#Mann=3,0
       0     .12       1     460    .055      11     508     .12      14
Bank Sta=460,508
Exp/Cntr=0.3,0.1

--- Wrk6_sol.g01 (geometry) ---

Geom Title=Imported Geom 01
ViewRect= 0, 1, 1, 0
Reach=1
Rch X Y Up & X Y Dn=0.5,0.9,0.5,0.1
Rch Arrow X Y Up & X Y Dn=0,0,0,0
Rch Type=0

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
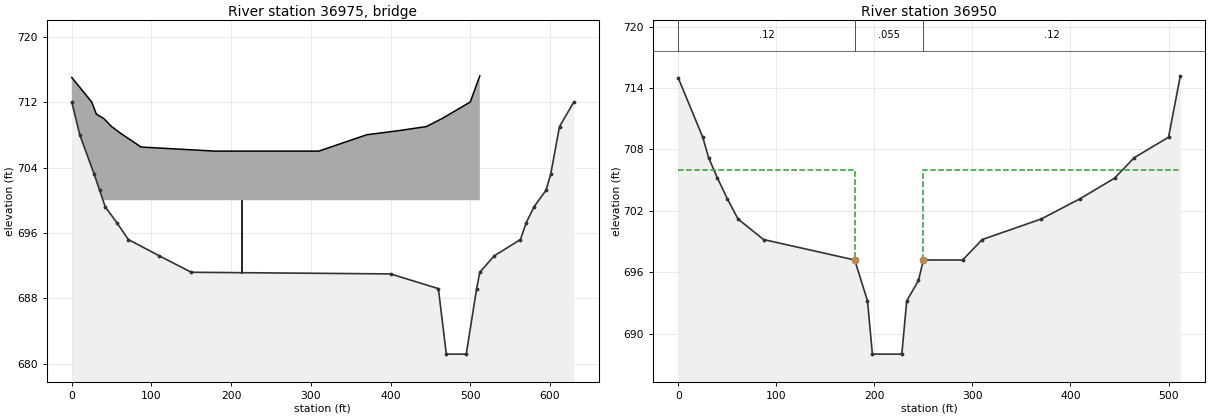
Type RM Length L Ch R =3,36975   ,,,,0,0,0
Node Desc=Bridge # 1
Bridge Culvert--1,-1,-1,-1
Deck Dist Width WeirC Skew NumUp NumDn MinLoCord MaxHiCord MaxSubmerge Is_Ogee
0,60,2.9,,16,16,706,,0.95,0
       0      25      31      40      50      61      87     180     290     310
     370     410     445     465     500     512
     715     712   710.5     710     709   708.2   706.5     706     706     706
     708   708.5     709     710     712   715.2
     700     700     700     700     700     700     700     700     700     700
     700     700     700     700     700     700
       0      25      31      40      50      61      87     180     290     310
     370     410     445     465     500     512
     715     712   710.5     710     709   708.2   706.5     706     706     706
     708   708.5     709     710     712   715.2
     700     700     700     700     700     700     700     700     700     700
     700     700     700     700     700     700
Pier Skew, UpSta & Num, DnSta & Num=,213, 2,213, 2, 0, 0
     1.5     1.5
     688     704
     1.5     1.5
     688     704
BR Coef= 0, 0,-1,0.9, 0,,,0.8164966,0,2,2,704

Type RM Length L Ch R =1,36950   ,700,750,800,0,0,0
Node Desc= 36950
#Sta/Elev= 22
       0     715      25   709.2      31   707.2      40   705.2      50   703.2
      61   701.2      87   699.2     180   697.2     193   693.2     198     688
     228     688     233   693.2     245   695.2     250   697.2     290   697.2
     310   699.2     370   701.2     410   703.2     445   705.2     465   707.2
     500   709.2     512   715.2
#Mann=3,0
       0     .12       0     180    .055       0     250     .12       0
#XS Ineff= 2 , 0
             180     706     250             706
Bank Sta=180,250
Exp/Cntr=0.3,0.1