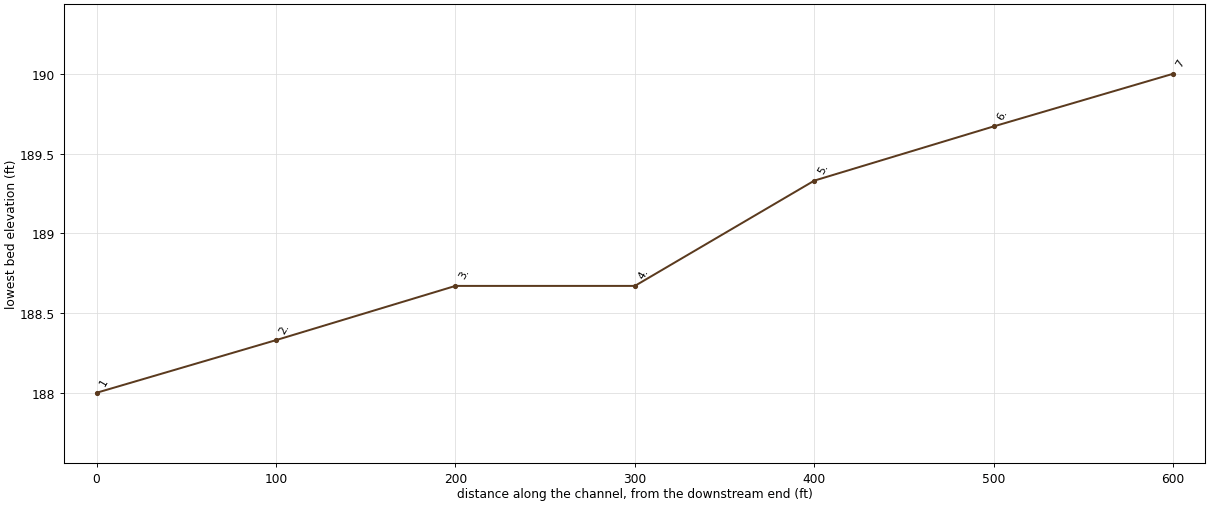
--- output1s.PRJ (project) ---

Proj Title=Output Analysis Solution # 1
Current Plan=p01
Default Exp/Contr=0.3,0.1
English Units
Geom File=g01
Flow File=f01
Plan File=p01

--- output1s.P01 (plan) ---

Plan Title=Output Analysis #1
Short Identifier=DISCUSSION #
Geom File=g01
Flow File=f01
Multiple Comp Mode
Subcritical Flow
K Sum by GR= 0
Std Step Tol= .01
Critical Tol= .01
Num of Std Step Trials= 20
Max Error Tol= .3
Flow Tol Ratio= .001
Log Output Level= 0
Friction Slope Method= 1
Calc Critical at every XS
Parabolic Critical Depth

--- output1s.F01 (steady flow) ---

Flow Title=Flow Data
Number of Flows and Profiles and Boundary= 1, 1, 1
Rch & RM=Reach 1     ,7
    2000
Boundary for Rch & Prof#=Reach 1     , 1
Up Type= 0
Up Value=0
Dn Type= 3
Dn Value=0.004

--- output1s.G01 (geometry) ---

Geom Title=Geometry Data
ViewRect= 0, 1, 1, 0
Reach=Reach 1
Rch X Y Up & X Y Dn=0.1994885,0.852459,0.6982097,0.2486339
Rch Arrow X Y Up & X Y Dn=0,0,0,0
Rch Type=0

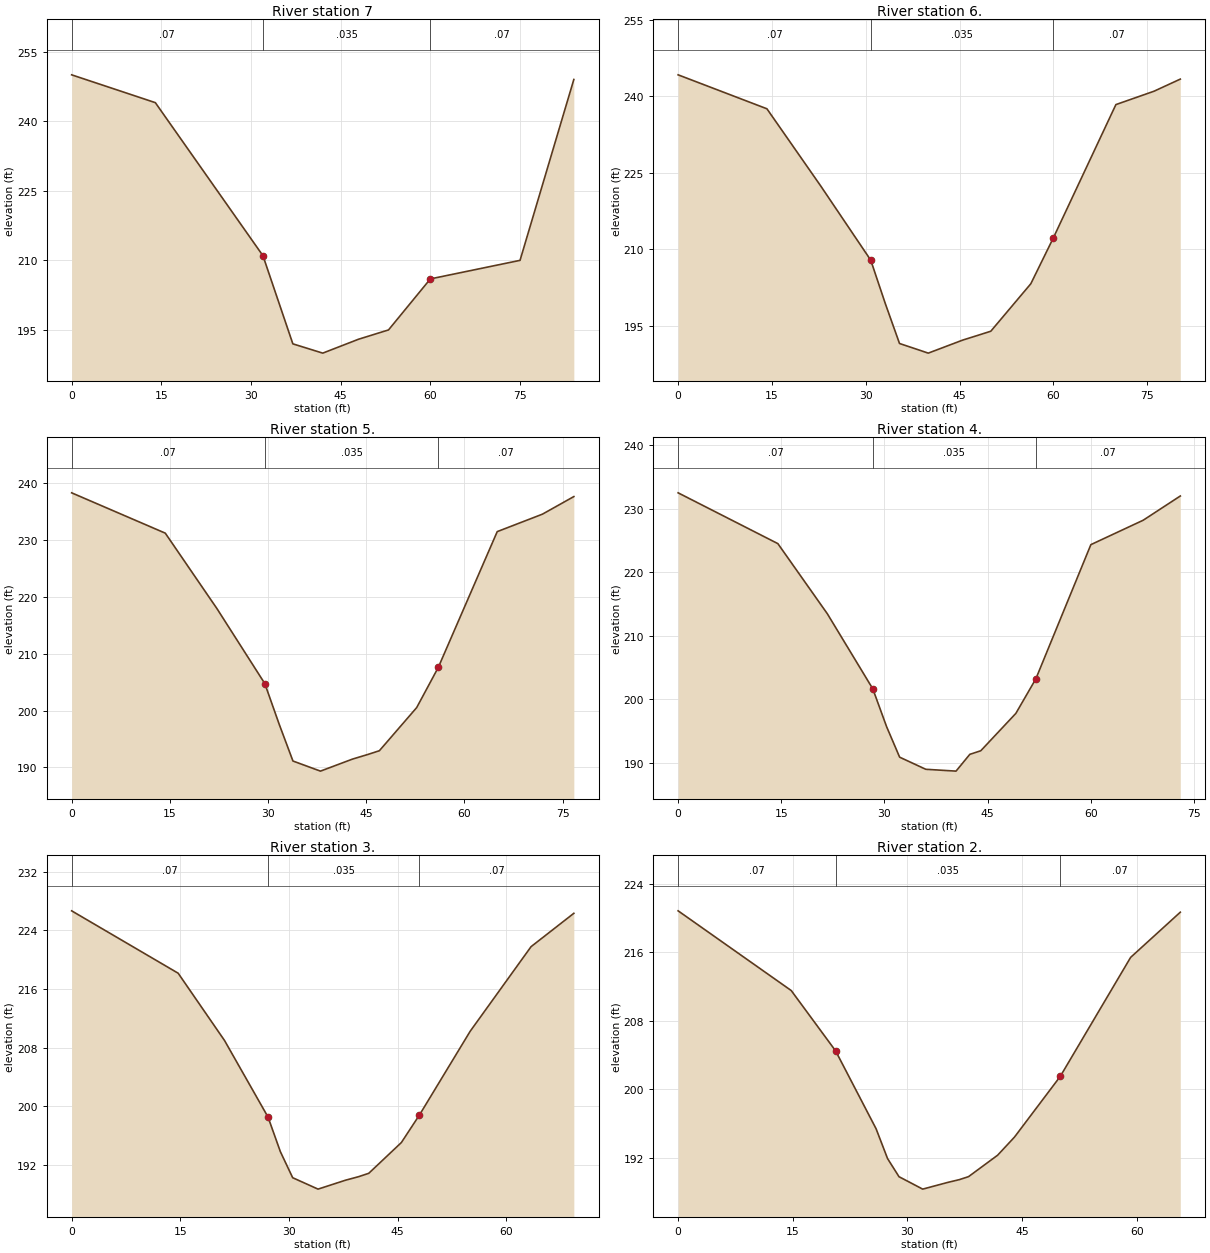
Type RM Length L Ch R =1,7       ,100,100,100,0,0,0
Node Desc=UPSTREAM LIMIT
#Sta/Elev= 10
       0     250      14     244      32     211      37     192      42     190
      48     193      53     195      60     206      75     210      84     249
#Mann=3,0
       0     .07       0      32    .035       0      60     .07       0
Bank Sta=32,60
Exp/Cntr=0.3,0.1

Type RM Length L Ch R =1,6.      ,100,100,100,0,0,0
Node Desc=SECTION 6
#Sta/Elev= 15
       0  244.17    14.2  237.52    22.8  222.41    30.8  207.88    33.1  199.48
    35.4  191.56      40  189.67    45.5  192.22      48  193.18      50  193.96
    56.4  203.26      60  212.24      70  238.34    76.1  240.96    80.3  243.33
#Mann=3,0
       0     .07       0    30.8    .035       0      60     .07       0
Bank Sta=30.8,60
Exp/Cntr=0.3,0.1

Type RM Length L Ch R =1,5.      ,100,100,100,0,0,0
Node Desc=SECTION 5
#Sta/Elev= 15
       0  238.33    14.3  231.23    22.2  217.93    29.5  204.75    31.7  197.58
    33.8  191.11      38  189.33    42.9  191.45    45.2  192.25      47  192.92
    52.7  200.52      56   207.6      65   231.5    71.9  234.57    76.7  237.67
#Mann=3,0
       0     .07       0    29.5    .035       0      56     .07       0
Bank Sta=29.5,56
Exp/Cntr=0.3,0.1

Type RM Length L Ch R =1,4.      ,100,100,100,0,0,0
Node Desc=SECTION 4
#Sta/Elev= 15
       0   232.5    14.5   224.5    21.7  213.44    28.3  201.63    30.3  195.69
    32.2  190.87      36  188.96    40.4  188.67    42.4  191.31      44  191.88
    49.1  197.77      52   203.2      60  224.34    67.6  228.18      73     232
#Mann=3,0
       0     .07       0    28.3    .035       0      52     .07       0
Bank Sta=28.3,52
Exp/Cntr=0.3,0.1

Type RM Length L Ch R =1,3.      ,100,100,100,0,0,0
Node Desc=SECTION 3
#Sta/Elev= 15
       0  226.67    14.7  218.15    21.1  208.96    27.1  198.51    28.8  193.79
    30.5  190.23      34  188.67    37.8  189.89    39.6  190.37      41  190.83
    45.5  195.03      48   198.8      55  210.23    63.4  221.78    69.3  226.33
#Mann=3,0
       0     .07       0    27.1    .035       0      48     .07       0
Bank Sta=27.1,48
Exp/Cntr=0.3,0.1

Type RM Length L Ch R =1,2.      ,100,100,100,0,0,0
Node Desc=SECTION 2
#Sta/Elev= 15
       0  220.83    14.8  211.52    20.6  204.48    25.9  195.38    27.4   191.9
    28.9  189.78      32  188.33    35.3  189.12    36.8  189.44      38  189.79
    41.8  192.29      44   194.4      50   201.5    59.2  215.39    65.7  220.67
#Mann=3,0
       0     .07       0    20.6    .035       0      50     .07       0
Bank Sta=20.6,50
Exp/Cntr=0.3,0.1

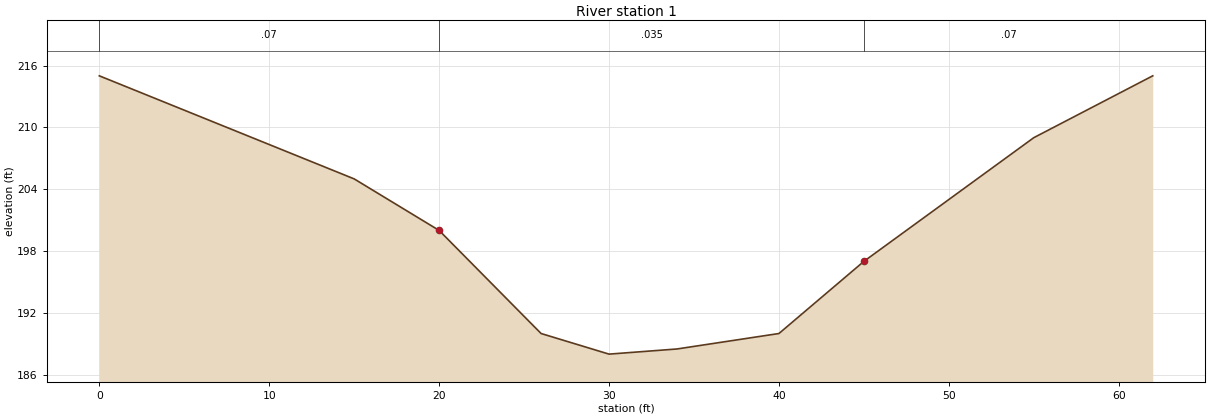
Type RM Length L Ch R =1,1       ,0,0,0,0,0,0
Node Desc=DOWNSTREAM LIMIT
#Sta/Elev= 10
       0     215      15     205      20     200      26     190      30     188
      34   188.5      40     190      45     197      55     209      62     215
#Mann=3,0
       0     .07       0      20    .035       0      45     .07       0
Bank Sta=20,45
Exp/Cntr=0.3,0.1