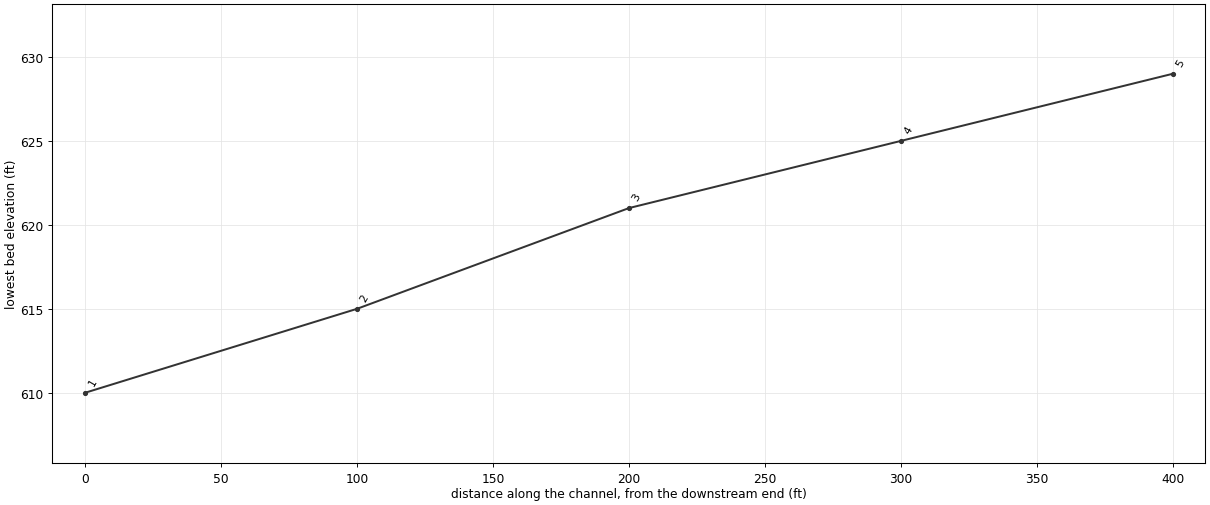
--- output2s.PRJ (project) ---

Proj Title=Output Analysis Solution # 2
Current Plan=p02
Default Exp/Contr=0.3,0.1
English Units
Geom File=g02
Flow File=f01
Plan File=p02
BEGIN DESCRIPTION:
END DESCRIPTION:

--- output2s.P02 (plan) ---

Plan Title=Output Analysis #2
Short Identifier=Plan 02
Geom File=g02
Flow File=f01
Interactive Comp Mode
Subcritical Flow
K Sum by GR= 0
Std Step Tol= 0.01
Critical Tol= 0.01
Num of Std Step Trials= 20
Max Error Tol= 0.3
Flow Tol Ratio= 0.001
Log Output Level= 0
Friction Slope Method= 1
Calc Critical at every XS
Global Vel Dist= 0 , 0 , 0
Encroach Param=-1 ,0,0, 0

--- output2s.F01 (steady flow) ---

Flow Title=Pine Creek Flow Data
Number of Flows and Profiles and Boundary= 1, 2, 1
Rch & RM=Pine Creek  ,5
    5450   17800
Boundary for Rch & Prof#=Pine Creek  , 1
Up Type= 0
Up Value=0
Dn Type= 1
Dn Value=624.3
Boundary for Rch & Prof#=Pine Creek  , 2
Up Type= 0
Up Value=0
Dn Type= 1
Dn Value=631.9

--- output2s.G02 (geometry) ---

Geom Title=Pine Creek Geometry Data
ViewRect= 0, 1, 1, 0
Reach=Pine Creek
Rch X Y Up & X Y Dn=0.168798,0.863388,0.8005115,0.1448087
Rch Arrow X Y Up & X Y Dn=0,0,0,0
Rch Type=0

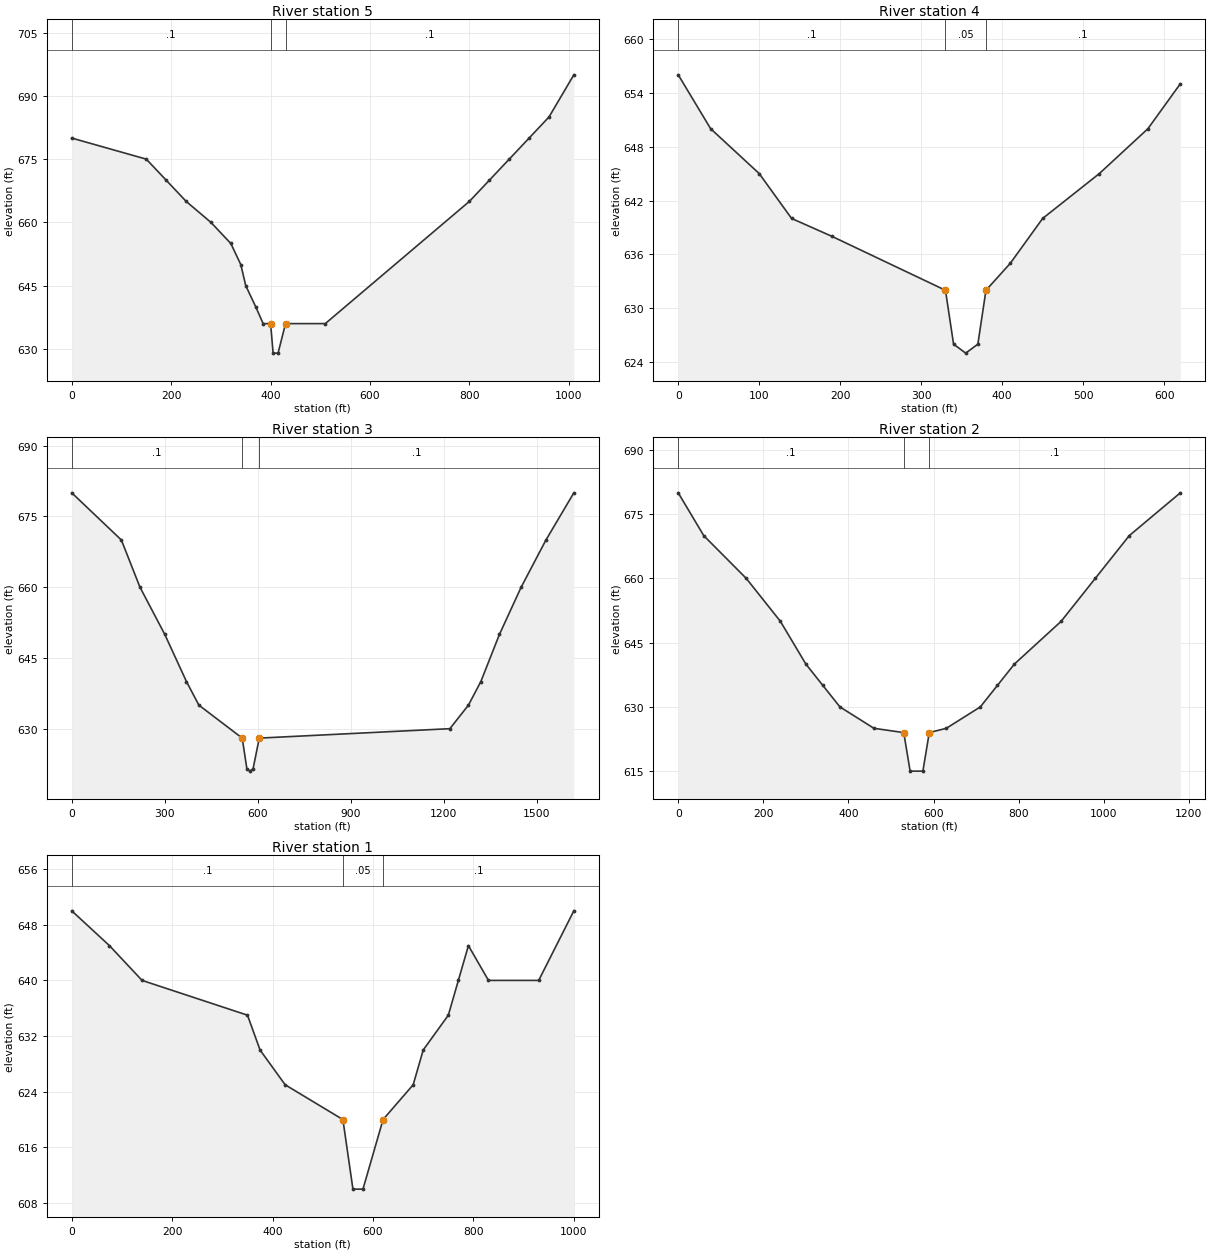
Type RM Length L Ch R =1,5       ,100,100,155,0,0,0
#Sta/Elev= 21
       0     680     150     675     190     670     230     665     280     660
     320     655     340     650     350     645     370     640     385     636
     400     636     405     629     415     629     430     636     510     636
     800     665     840     670     880     675     920     680     960     685
    1010     695
#Mann=3,0
       0      .1       0     400     .05       0     430      .1       0
Bank Sta=400,430
Exp/Cntr=0.3,0.1

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
Type RM Length L Ch R =1,4       ,109.0909,100,81.81818,0,0,0
#Sta/Elev= 15
       0     656      40     650     100     645     140     640     190     638
     330     632     340     626     355     625     370     626     380     632
     410     635     450     640     520     645     580     650     620     655
#Mann=3,0
       0      .1       0     330     .05       0     380      .1       0
Bank Sta=330,380
Exp/Cntr=0.3,0.1

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
Type RM Length L Ch R =1,3       ,100,100,100,0,0,0
#Sta/Elev= 18
       0     680     160     670     220     660     300     650     370     640
     410     635     550     628     565   621.5     575     621     585   621.5
     605     628    1220     630    1280     635    1320     640    1380     650
    1450     660    1530     670    1620     680
#Mann=3,0
       0      .1       0     550    .045       0     605      .1       0
Bank Sta=550,605
Exp/Cntr=0.3,0.1

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
Type RM Length L Ch R =1,2       ,79.41177,100,102.9412,0,0,0
#Sta/Elev= 20
       0     680      60     670     160     660     240     650     300     640
     340     635     380     630     460     625     530     624     545     615
     575     615     590     624     630     625     710     630     750     635
     790     640     900     650     980     660    1060     670    1180     680
#Mann=3,0
       0      .1       0     530    .045       0     590      .1       0
Bank Sta=530,590
Exp/Cntr=0.3,0.1

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
Type RM Length L Ch R =1,1       ,0,0,0,0,0,0
Node Desc=Downstream Cross-section
#Sta/Elev= 18
       0     650      75     645     140     640     350     635     375     630
     425     625     540     620     560     610     580     610     620     620
     680     625     700     630     750     635     770     640     790     645
     830     640     930     640    1000     650
#Mann=3,0
       0      .1       0     540     .05       0     620      .1       0
Bank Sta=540,620
Exp/Cntr=0.3,0.1