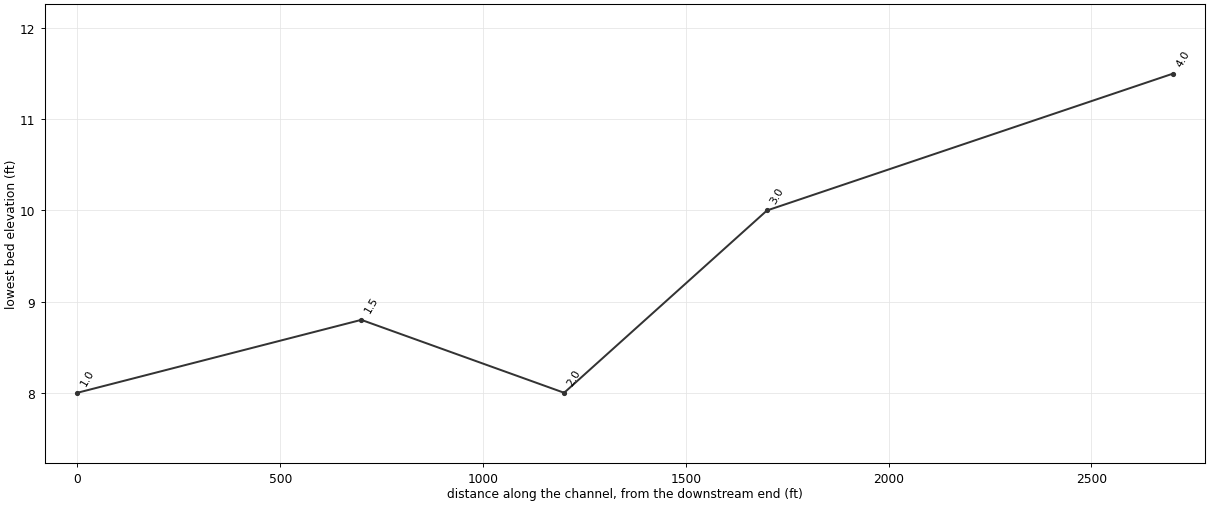
--- output3s.PRJ (project) ---

Proj Title=Output Analysis Solution # 3
Current Plan=p01
Default Exp/Contr=0.3,0.1
English Units
Geom File=g01
Flow File=f01
Plan File=p01

--- output3s.P01 (plan) ---

Plan Title=Easy Creek
Geom File=g01
Flow File=f01
Multiple Comp Mode
Subcritical Flow
K Sum by GR= 0
Std Step Tol= .01
Critical Tol= .01
Num of Std Step Trials= 20
Max Error Tol= .3
Flow Tol Ratio= .001
Log Output Level= 0
Friction Slope Method= 1
Parabolic Critical Depth

--- output3s.F01 (steady flow) ---

Flow Title=Easy Creek Flow Data
Number of Flows and Profiles and Boundary= 1, 1, 1
Rch & RM=Easy Creek  ,4.0
    1500
Boundary for Rch & Prof#=Easy Creek  , 1
Up Type= 0
Up Value=0
Dn Type= 1
Dn Value=15.5

--- output3s.G01 (geometry) ---

Geom Title=Easy Creek Geometry
ViewRect= 0, 1, 1, 0
Reach=Easy Creek
Rch X Y Up & X Y Dn=0.2073579,0.9107143,0.7491639,0.1629464
Rch Arrow X Y Up & X Y Dn=0,0,0,0
Rch Type=0

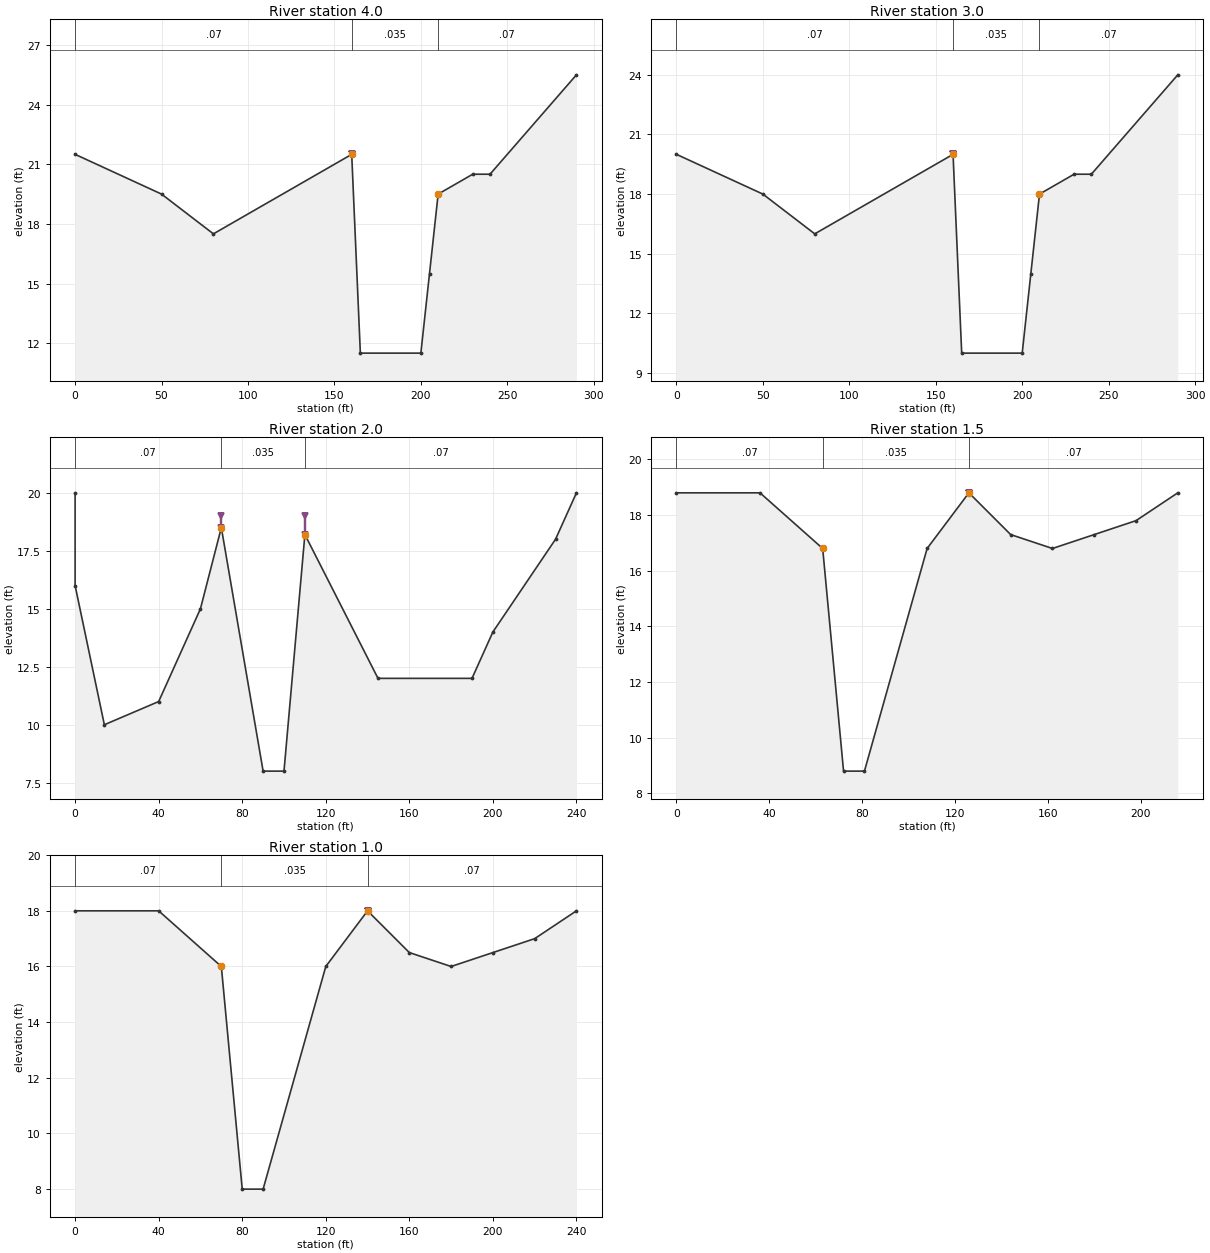
Type RM Length L Ch R =1,4.0     ,1000,1000,1000,0,0,0
#Sta/Elev= 11
       0    21.5      50    19.5      80    17.5     160    21.5     165    11.5
     200    11.5     205    15.5     210    19.5     230    20.5     240    20.5
     290    25.5
#Mann=3,0
       0     .07       0     160    .035       0     210     .07       0
Levee=-1,160,21.5,0,,
Bank Sta=160,210
Exp/Cntr=0.3,0.1

Type RM Length L Ch R =1,3.0     ,500,500,500,0,0,0
#Sta/Elev= 11
       0      20      50      18      80      16     160      20     165      10
     200      10     205      14     210      18     230      19     240      19
     290      24
#Mann=3,0
       0     .07       0     160    .035       0     210     .07       0
Levee=-1,160,20,0,,
Bank Sta=160,210
Exp/Cntr=0.3,0.1

Type RM Length L Ch R =1,2.0     ,500,500,500,0,0,0
#Sta/Elev= 14
       0      20       0      16      14      10      40      11      60      15
      70    18.5      90       8     100       8     110    18.2     145      12
     190      12     200      14     230      18     240      20
#Mann=3,0
       0     .07       0      70    .035       0     110     .07       0
Levee=-1,70,19,-1,110,19
Bank Sta=70,110
Exp/Cntr=0.3,0.1

Type RM Length L Ch R =1,1.5     ,700,700,700,0,0,0
Node Desc=Section 1.5
#Sta/Elev= 12
       0    18.8      36    18.8      63    16.8      72     8.8      81     8.8
     108    16.8     126    18.8     144    17.3     162    16.8     180    17.3
     198    17.8     216    18.8
#Mann=3,0
       0     .07       0      63    .035       0     126     .07       0
Levee=0,,,-1,126,18.8
Bank Sta=63,126
Exp/Cntr=0.3,0.1

Type RM Length L Ch R =1,1.0     ,0,0,0,0,0,0
Node Desc=Section 1 [Downstream]
#Sta/Elev= 12
       0      18      40      18      70      16      80       8      90       8
     120      16     140      18     160    16.5     180      16     200    16.5
     220      17     240      18
#Mann=3,0
       0     .07       0      70    .035       0     140     .07       0
Levee=0,,,-1,140,18
Bank Sta=70,140
Exp/Cntr=0.3,0.1