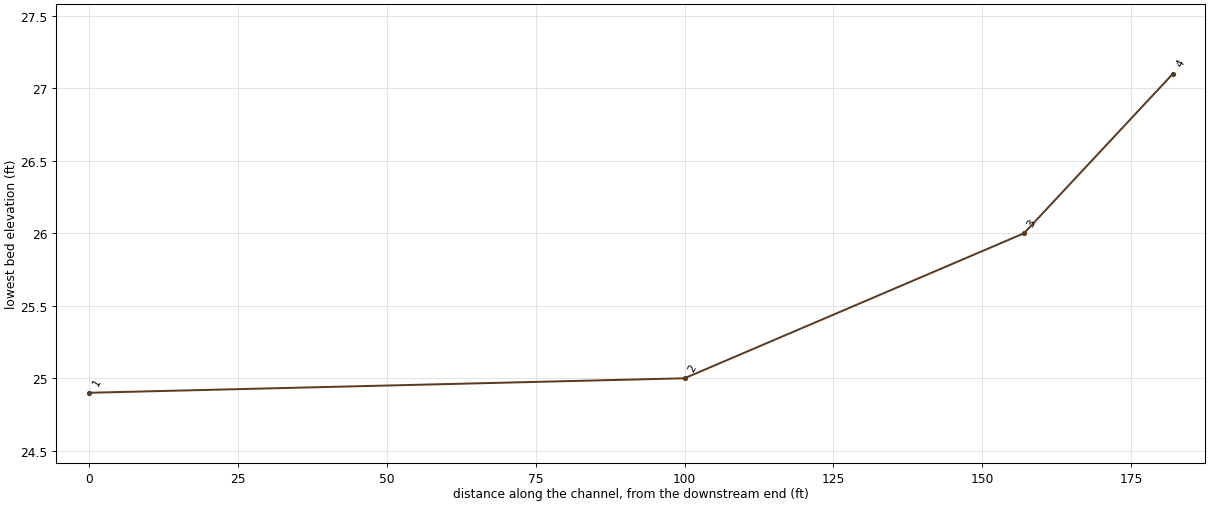
--- output4s.PRJ (project) ---

Proj Title=Output Analysis Solution # 4
Current Plan=p01
Default Exp/Contr=0.3,0.1
English Units
Geom File=g01
Flow File=f01
Plan File=p01

--- output4s.P01 (plan) ---

Plan Title=Output Analysis #4
Short Identifier=Plan 01
Geom File=g01
Flow File=f01
Multiple Comp Mode
Subcritical Flow
K Sum by GR=-1
Std Step Tol= .01
Critical Tol= .01
Num of Std Step Trials= 20
Max Error Tol= .3
Flow Tol Ratio= .01
Log Output Level= 0
Friction Slope Method= 1
Parabolic Critical Depth

--- output4s.F01 (steady flow) ---

Flow Title=Flow Data
Number of Flows and Profiles and Boundary= 1, 2, 1
Rch & RM=1           ,4
     200     280
Boundary for Rch & Prof#=1           , 1
Up Type= 0
Up Value=0
Dn Type= 3
Dn Value=0.001
Boundary for Rch & Prof#=1           , 2
Up Type= 0
Up Value=0
Dn Type= 3
Dn Value=0.001

--- output4s.G01 (geometry) ---

Geom Title=Geometry Data
ViewRect= 0, 1, 1, 0
Reach=1
Rch X Y Up & X Y Dn=0.5,0.9,0.5,0.1
Rch Arrow X Y Up & X Y Dn=0,0,0,0
Rch Type=0

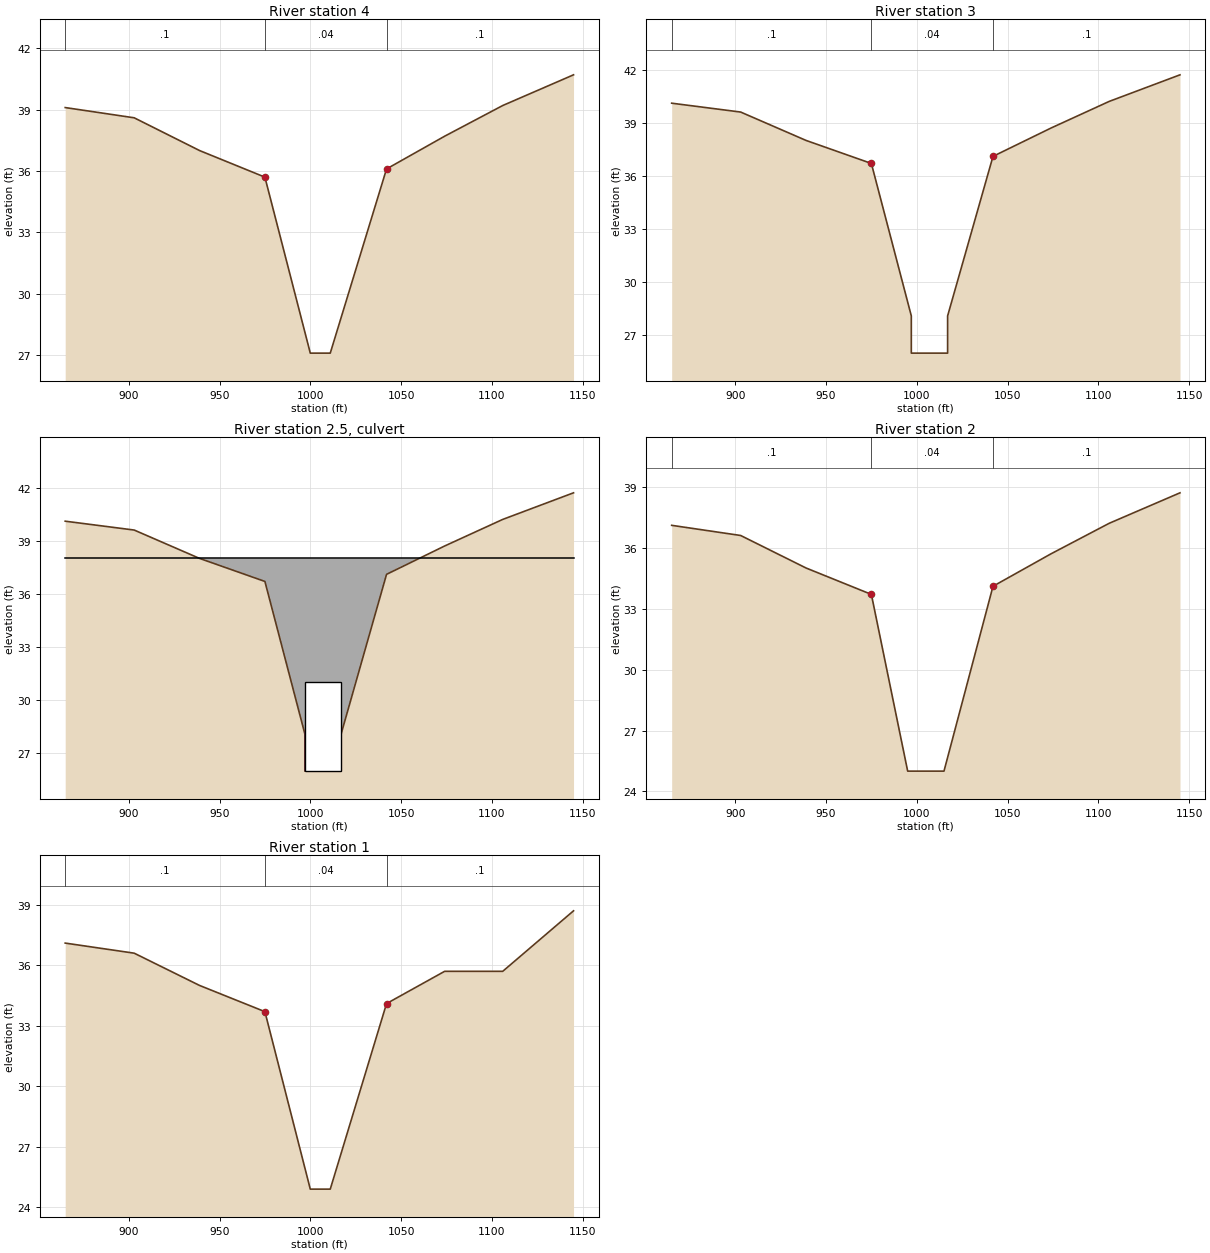
Type RM Length L Ch R =1,4       ,25,25,25,0,0,0
Node Desc= 4
#Sta/Elev= 10
     865    39.1     903    38.6     939      37     975    35.7    1000    27.1
    1011    27.1    1042    36.1    1074    37.7    1106    39.2    1145    40.7
#Mann=3,0
     865      .1       0     975     .04       0    1042      .1       0
Bank Sta=975,1042
Exp/Cntr=0.5,0.3

Type RM Length L Ch R =1,3       ,57,57,57,0,0,0
Node Desc= 3
#Sta/Elev= 12
     865    40.1     903    39.6     939      38     975    36.7     997    28.1
     997      26    1017      26    1017    28.1    1042    37.1    1074    38.7
    1106    40.2    1145    41.7
#Mann=3,1
     865      .1       1     975     .04       4    1042      .1       9
Bank Sta=975,1042
Exp/Cntr=0.5,0.3

Type RM Length L Ch R =2,2.5     ,50,50,50,0,0,0
Node Desc=one pipe culvert
Bridge Culvert-0,0,-1,-1
Deck Dist Width WeirC Skew NumUp NumDn MinLoCord MaxHiCord MaxSubmerge Is_Ogee
5,50,3,0,4,4,,,0.95,0
     865     903    1106    1145
      38      38      38      38
      25      25      25      25
     865     903    1106    1145
      36      36      36      36
      25      25      25      25
Culvert=2,5,20,50,0.012,0.5,1,10,1,26,1007,25,1005,Culvert # 1 , 0

Type RM Length L Ch R =1,2       ,100,100,100,0,0,0
Node Desc= 2
#Sta/Elev= 12
     865    37.1     903    36.6     939      35     975    33.7     995      25
    1003      25    1010      25    1015      25    1042    34.1    1074    35.7
    1106    37.2    1145    38.7
#Mann=3,1
     865      .1       1     975     .04       4    1042      .1       9
Bank Sta=975,1042
Exp/Cntr=0.5,0.3

Type RM Length L Ch R =1,1       ,0,0,0,0,0,0
Node Desc= 1
#Sta/Elev= 10
     865    37.1     903    36.6     939      35     975    33.7    1000    24.9
    1011    24.9    1042    34.1    1074    35.7    1106    35.7    1145    38.7
#Mann=3,0
     865      .1       0     975     .04       0    1042      .1       0
Bank Sta=975,1042
Exp/Cntr=0.3,0.1