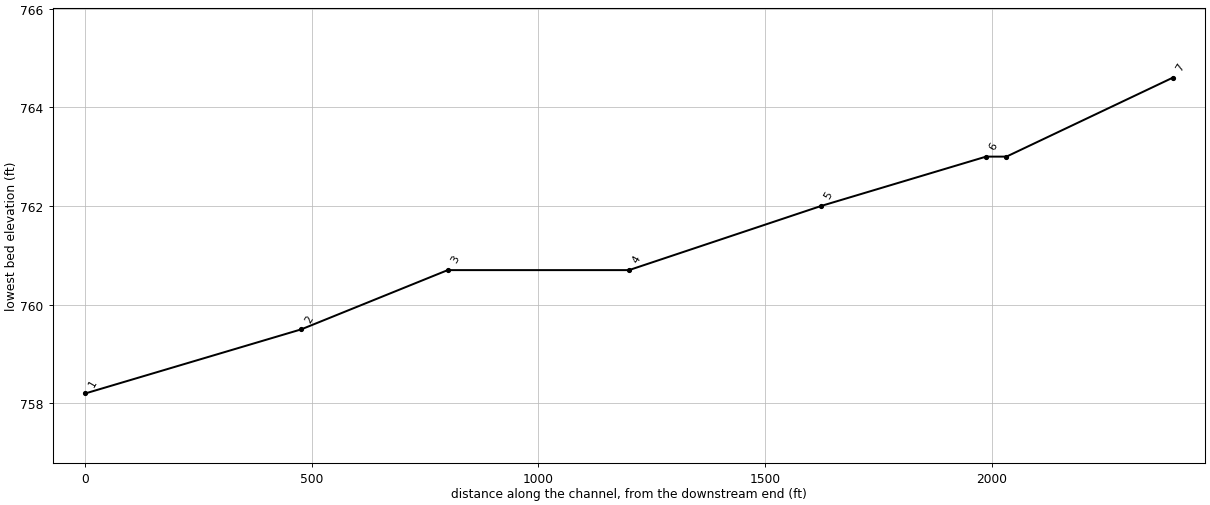
--- output6s.PRJ (project) ---

Proj Title=Output Analysis Solution # 6
Current Plan=p02
Default Exp/Contr=0.3,0.1
English Units
Geom File=g02
Flow File=f02
Plan File=p02

--- output6s.P02 (plan) ---

Plan Title=Output Analysis #6
Short Identifier=Imported Pla
Geom File=g02
Flow File=f02
Multiple Comp Mode
Subcritical Flow
K Sum by GR= 0
Std Step Tol= .01
Critical Tol= .01
Num of Std Step Trials= 20
Max Error Tol= .3
Flow Tol Ratio= .001
Log Output Level= 0
Friction Slope Method= 1
Parabolic Critical Depth

--- output6s.F02 (steady flow) ---

Flow Title=Flow Data
Number of Flows and Profiles and Boundary= 2, 3, 1
Rch & RM=1           ,7
   15234   24350   45000
Rch & RM=1           ,4
   18789   28500   50000
Boundary for Rch & Prof#=1           , 1
Up Type= 32767
Up Value=0
Dn Type= 3
Dn Value=0.001
Boundary for Rch & Prof#=1           , 2
Up Type= 32767
Up Value=0
Dn Type= 3
Dn Value=0.001
Boundary for Rch & Prof#=1           , 3
Up Type= 32767
Up Value=0
Dn Type= 3
Dn Value=0.001

--- output6s.G02 (geometry) ---

Geom Title=Geometry Data
ViewRect= 0, 1, 1, 0
Reach=1
Rch X Y Up & X Y Dn=0.5,0.9,0.5,0.1
Rch Arrow X Y Up & X Y Dn=0,0,0,0
Rch Type=0

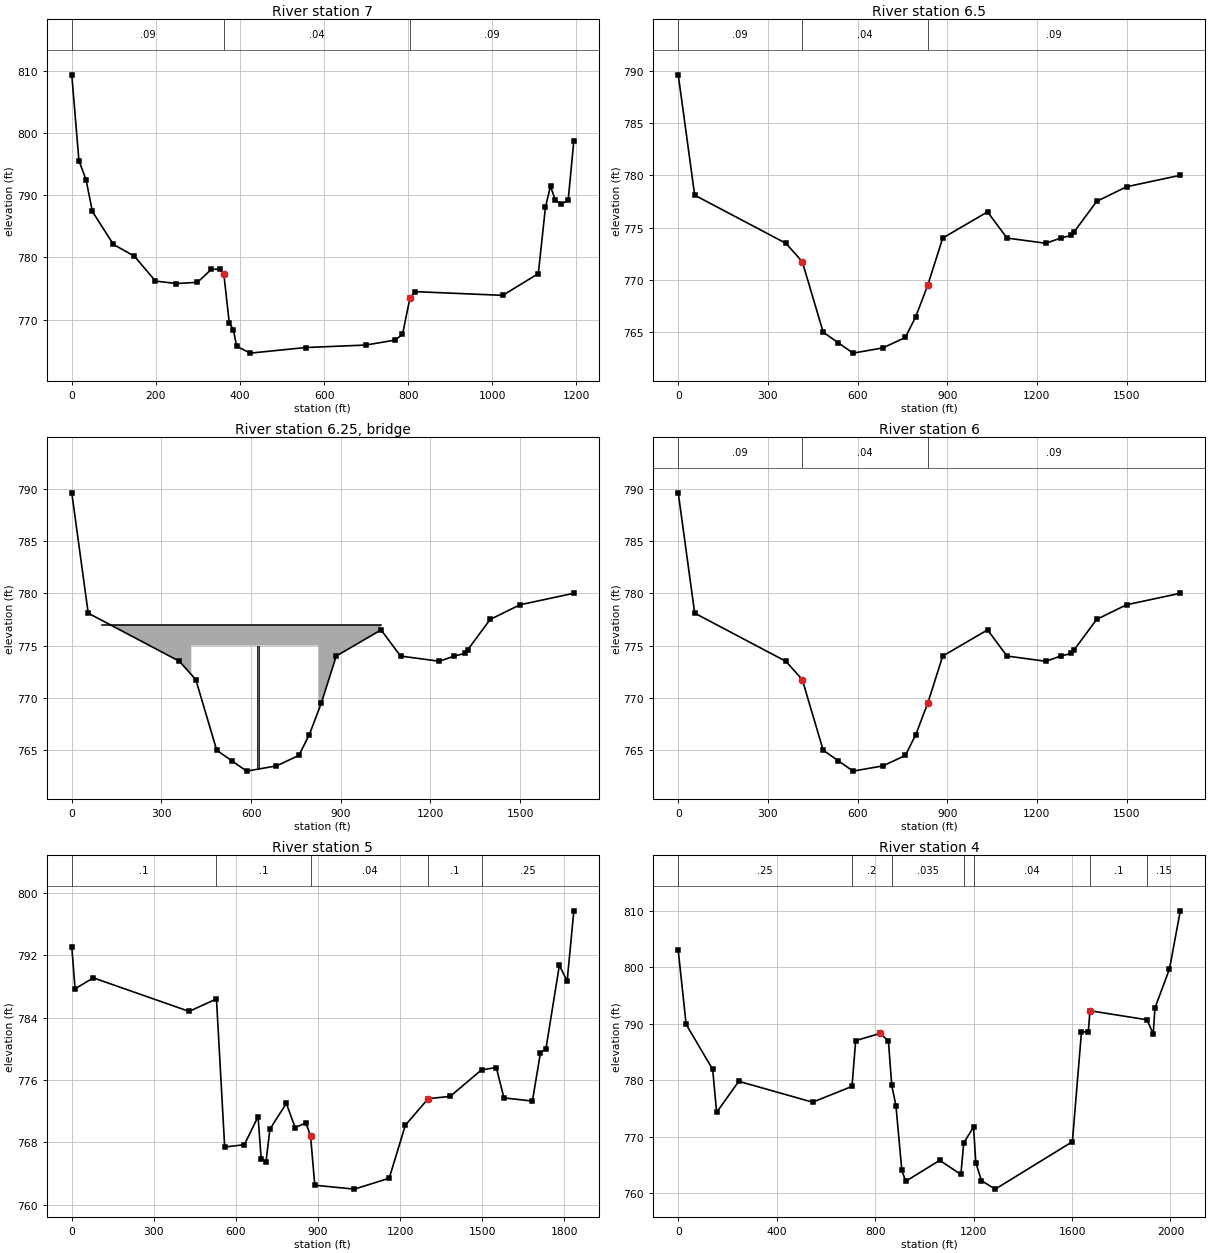
Type RM Length L Ch R =1,7       ,367,367,367,0,0,0
Node Desc= 0
#Sta/Elev= 30
       0   809.4      17   795.6      34   792.5      49   787.4      99   782.1
     149   780.2     199   776.2     249   775.8     299     776     332   778.1
     352   778.1   361.5   777.4   374.5   769.5   384.5   768.3     392   765.7
   424.5   764.6     556   765.5     699   765.9     769   766.7   786.5   767.6
     804   773.4   816.5   774.5    1025   773.9  1109.5   777.4  1126.5   788.1
  1138.5   791.5    1150   789.2    1164   788.6  1180.5   789.2    1194   798.8
#Mann=3,0
       0     .09       0   361.5     .04       0     804     .09       0
Bank Sta=361.5,804
Exp/Cntr=0.3,0.1

Type RM Length L Ch R =1,6.5     ,45,45,45,0,0,0
Node Desc= 412.5
#Sta/Elev= 21
       0   789.6      55   778.1     360   773.5     415  771.75     485     765
     535     764     585     763     685   763.5     760   764.5     795   766.5
     835   769.5     885     774    1035   776.5    1100     774    1230   773.5
    1280     774    1315  774.25    1325   774.6    1400   777.5    1500   778.9
    1680     780
#Mann=3,0
       0     .09       0     415     .04       0     835     .09       0
Bank Sta=415,835
Exp/Cntr=0.5,0.3

Type RM Length L Ch R =3,6.25    ,,,,0,0,0
Node Desc=bridge
Bridge Culvert--1,-1,-1,-1
Deck Dist Width WeirC Skew NumUp NumDn MinLoCord MaxHiCord MaxSubmerge Is_Ogee
10,25,2.2,,6,6,,,0.95,0
     100     400     400     825     825    1035
     777     777     777     777     777     777
             775     775     775     775
     100     400     400     825     825    1035
     777     777     777     777     777     777
             775     775     775     775
Pier Skew, UpSta & Num, DnSta & Num=,623, 2,623, 2, 0, 0
       6       6
     760     775
       6       6
     760     775
BR Coef=-1,-1,-1,0.85, 0,,,,-1,1.33,0,

Type RM Length L Ch R =1,6       ,364,364,364,0,0,0
Node Desc= 412.5
#Sta/Elev= 21
       0   789.6      55   778.1     360   773.5     415  771.75     485     765
     535     764     585     763     685   763.5     760   764.5     795   766.5
     835   769.5     885     774    1035   776.5    1100     774    1230   773.5
    1280     774    1315  774.25    1325   774.6    1400   777.5    1500   778.9
    1680     780
#Mann=3,0
       0     .09       0     415     .04       0     835     .09       0
Bank Sta=415,835
Exp/Cntr=0.3,0.1

Type RM Length L Ch R =1,5       ,424,424,424,0,0,0
Node Desc= 776.23
#Sta/Elev= 30
       0   793.1      12   787.7      79   789.1     429   784.8     529   786.4
     559   767.4     631   767.7     681   771.3   692.5   765.9     710   765.5
   724.5   769.7   784.5     773   816.5   769.9     856   770.5     873   768.8
   888.5   762.5  1033.5     762  1160.5   763.4  1219.5   770.2    1303   773.6
  1383.5   773.9    1498   777.3    1552   777.6    1580   773.7    1684   773.3
  1713.5   779.5  1733.5     780  1782.5   790.7    1811   788.7  1835.5   797.7
#Mann=5,-1
       0      .1       1     529      .1      15     873     .04      30
    1303      .1      41    1498     .25      45
Bank Sta=873,1303
Exp/Cntr=0.3,0.1

Type RM Length L Ch R =1,4       ,400,400,400,0,0,0
Node Desc= 1200
#Sta/Elev= 30
       0     803      32   789.9     140   781.9     156   774.3     246   779.8
     546   776.1     706   778.9     721     787     821   788.3     854   786.9
   867.5   779.1   884.5   775.5   908.5     764   924.5   762.1  1062.5   765.8
  1148.5   763.3    1160   768.9    1200   771.7    1209   765.4    1232   762.2
    1288   760.7  1601.5   769.1  1638.5   788.6    1666   788.5    1673   792.3
  1904.5   790.7    1930   788.2    1937   792.8    1996   799.7    2040     810
#Mann=7,-1
       0     .25       1     706      .2      20   867.5    .035      25
    1160      .1      38    1200     .04      40    1673      .1      57
  1904.5     .15      65
Bank Sta=821,1673
Exp/Cntr=0.3,0.1

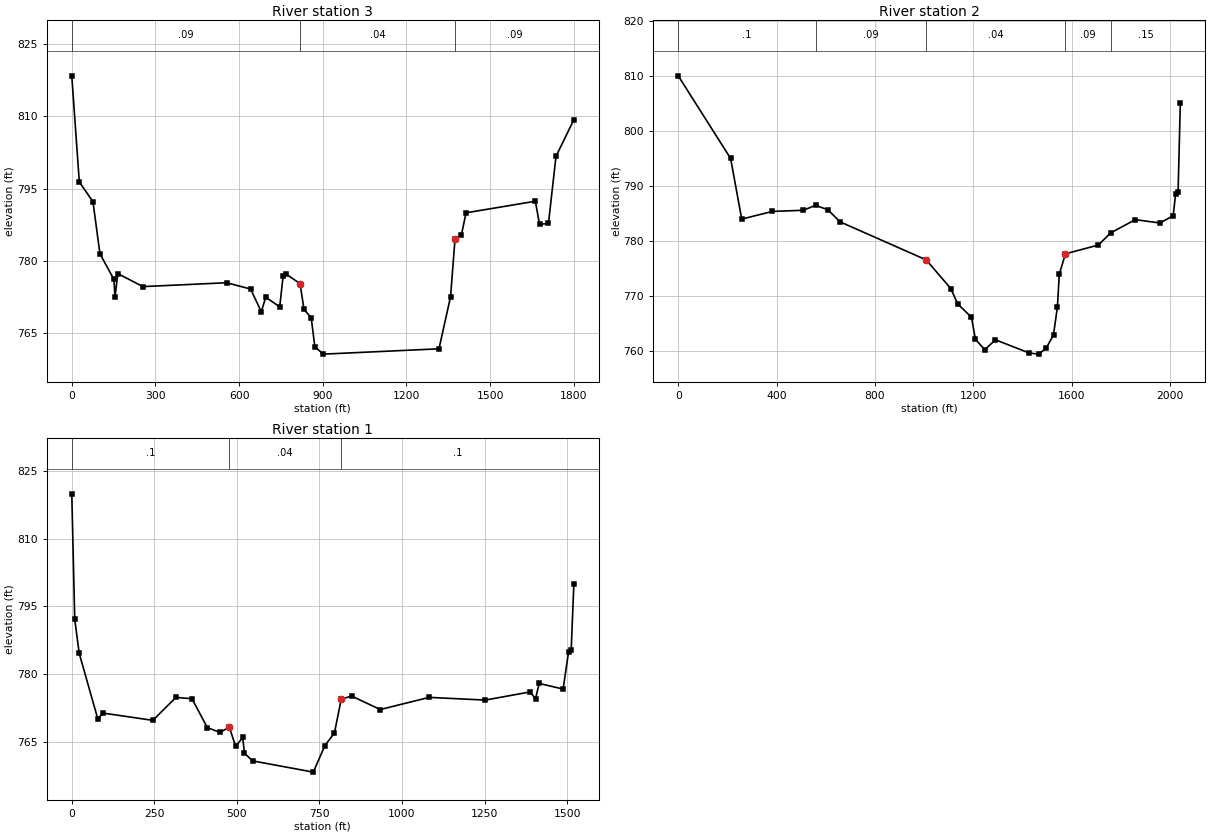
Type RM Length L Ch R =1,3       ,323,323,323,0,0,0
Node Desc= 1600
#Sta/Elev= 30
       0   818.4      27   796.4      76   792.3     101   781.5     151   776.2
     155   772.5     165   777.4     255   774.7     555   775.5     641   774.2
   679.5   769.5   695.5   772.5   745.5   770.5   757.5   776.8   768.5   777.3
   818.5   775.3   832.5     770   858.5   768.2   871.5   762.2     902   760.7
  1316.5   761.8    1358   772.6    1374   784.6  1396.5   785.3  1413.5     790
    1662   792.4    1677   787.6    1709   787.8    1736   801.7    1800   809.3
#Mann=3,0
       0     .09       1   818.5     .04      29    1374     .09      47
Bank Sta=818.5,1374
Exp/Cntr=0.3,0.1

Type RM Length L Ch R =1,2       ,477,477,477,0,0,0
Node Desc= 1923
#Sta/Elev= 30
       0     810     213     795     258     784     383   785.4     508   785.6
     558   786.5     608   785.7     658   783.5    1008   776.6    1108   771.4
    1136   768.6    1192   766.2    1208   762.2    1246   760.3  1289.5   762.1
    1427   759.7  1465.5   759.5    1496   760.6  1525.5     763  1541.5   768.1
    1549     774    1574   777.7    1708   779.3    1758   781.5    1858   783.9
    1958   783.3    2012   784.6    2022   788.6    2032     789    2041     805
#Mann=5,1
       0      .1       1     558     .09      10    1008     .04      19
    1574     .09      37    1758     .15      42
Bank Sta=1008,1574
Exp/Cntr=0.3,0.1

Type RM Length L Ch R =1,1       ,0,0,0,0,0,0
Node Desc= 2400
#Sta/Elev= 30
       0     820       9   792.1    22.5   784.6    78.5   770.1    95.5   771.3
   245.5   769.7   315.5   774.8     364   774.5   410.5   768.1     449     767
     477   768.2   496.5   763.9   517.5   765.9     523   762.4   547.5   760.7
   731.5   758.2   766.5   764.1   795.5   766.9     816   774.4   847.5   775.1
     934   772.1  1082.5   774.8    1252   774.2  1387.5     776  1404.5   774.5
  1415.5   777.9    1488  776.64  1504.5   784.9  1512.5   785.3  1520.5     800
#Mann=3,1
       0      .1       1     477     .04      19     816      .1      32
Bank Sta=477,816
Exp/Cntr=0.3,0.1